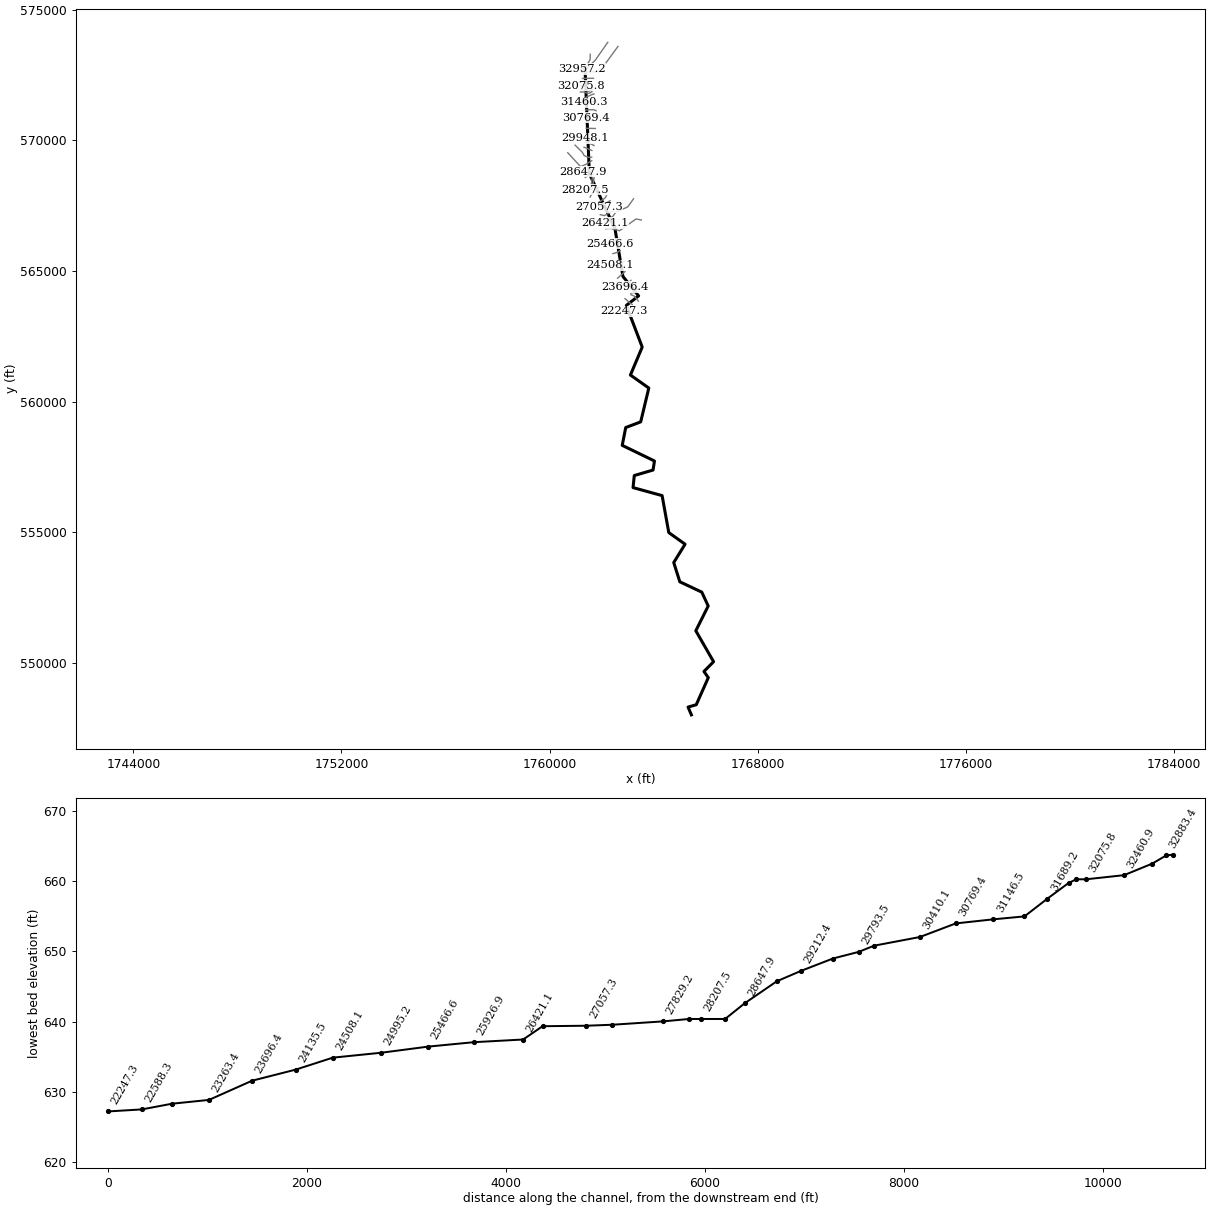
--- FROGCK.prj (project) ---

Proj Title=FROGCK
Current Plan=p01
Default Exp/Contr=0,0
English Units
Geom File=g01
Flow File=f01
Plan File=p01
BEGIN DESCRIPTION:
END DESCRIPTION:
DSS Export Rating Curves= 0
DSS Export Rating Curve Sorted= 0
DSS Export Volume Flow Curves= 0
DXF OffsetX= 0
DXF OffsetY= 0
DXF ScaleX= 0
DXF ScaleY= 0

--- FROGCK.p01 (plan) ---

Plan Title=Floodplain
Program Version=4.00
Geom File=g01
Flow File=f01
K Sum by GR=0
Std Step Tol=0.01
Critical Tol=0.01
Num of Std Step Trials=20
Max Error Tol=0.3
Flow Tol Ratio=0.001
Split Flow NTrial=30
Split Flow Tol=0.02
Split Flow Ratio=0.02
Log Output Level=0
Friction Slope Method=1
Unsteady Friction Slope Method=2
Unsteady Bridges Friction Slope Method=1
Global Log Level=0
CheckData=False
Run HTab=0
Run UNet=0
Run PostProcess=0
UNET Theta=0
UNET Theta Warmup=0
UNET ZTol=0
UNET ZSATol=0
UNET MxIter=0
UNET MaxInSteps=0
UNET DtIC=0
UNET DtMin=0
UNET MaxCRTS=0
UNET WFStab=0
UNET SFStab=0
UNET WFX=0
UNET SFX=0
UNET DSS MLevel=0
UNET DZMax Abort=0
UNET Convert EG Bridges=0
UNET Use Existing IB Tables=0
UNET Froude Limit=0
UNET Froude Power=0
Write IC File=0
Echo Input=False
Echo Output=False
Write Detailed=0

--- FROGCK.f01 (steady flow) ---

Flow Title=NFF Regression Equation
Program Version=4.10
Number of Profiles= 1
Profile Names=P100yr
River Rch & RM=FROGCK,Main            ,32957.2
798.2161
River Rch & RM=FROGCK,Main            ,32460.9
1212.405
River Rch & RM=FROGCK,Main            ,28647.9
1656.505
River Rch & RM=FROGCK,Main            ,26421.1
1747.782
River Rch & RM=FROGCK,Main            ,25466.6
2016.485
River Rch & RM=FROGCK,Main            ,24135.5
 2084.55
River Rch & RM=FROGCK,Main            ,18497.6
 2303.96
River Rch & RM=FROGCK,Main            ,9848.9
2517.143
River Rch & RM=FROGCK,Main            ,101.2
2775.445
Boundary for River Rch & Prof#=FROGCK,Main            , 1
Up Type= 0
Dn Type= 3
Dn Slope=0.0004
DSS Import GetInterval= 0
DSS Import GetPeak= 0
DSS Import FillOption= 0

--- FROGCK.g01 (geometry) ---

Geom Title=USGS 10m DEM
Program Version=4.10

River Reach=FROGCK          ,Main
Reach XY= 30
     1761361.264      572795.933      1761530.73      568722.764
     1762516.133      566615.494     1762822.557      564788.237
     1763424.987      564045.182     1762952.765      563680.598
     1763563.323      562085.715     1763109.883      561016.536
     1763816.915       560519.14     1763504.852      559224.459
     1762929.182       559007.02     1762794.632      558326.004
     1764034.362      557727.473     1763979.675      557381.119
     1763258.349      557170.909     1763211.126      556709.103
     1764328.487      556402.853     1764585.144       554987.89
     1765211.446      554542.577      1764775.71      553841.742
     1765009.623      553105.078     1765854.969      552708.811
     1766100.622      552178.626     1765624.206       551231.38
       1766307.8      550047.786     1765937.515      549673.187
     1766104.675      549438.411     1765641.133       548400.65
     1765326.029      548310.807     1765455.571      548012.771

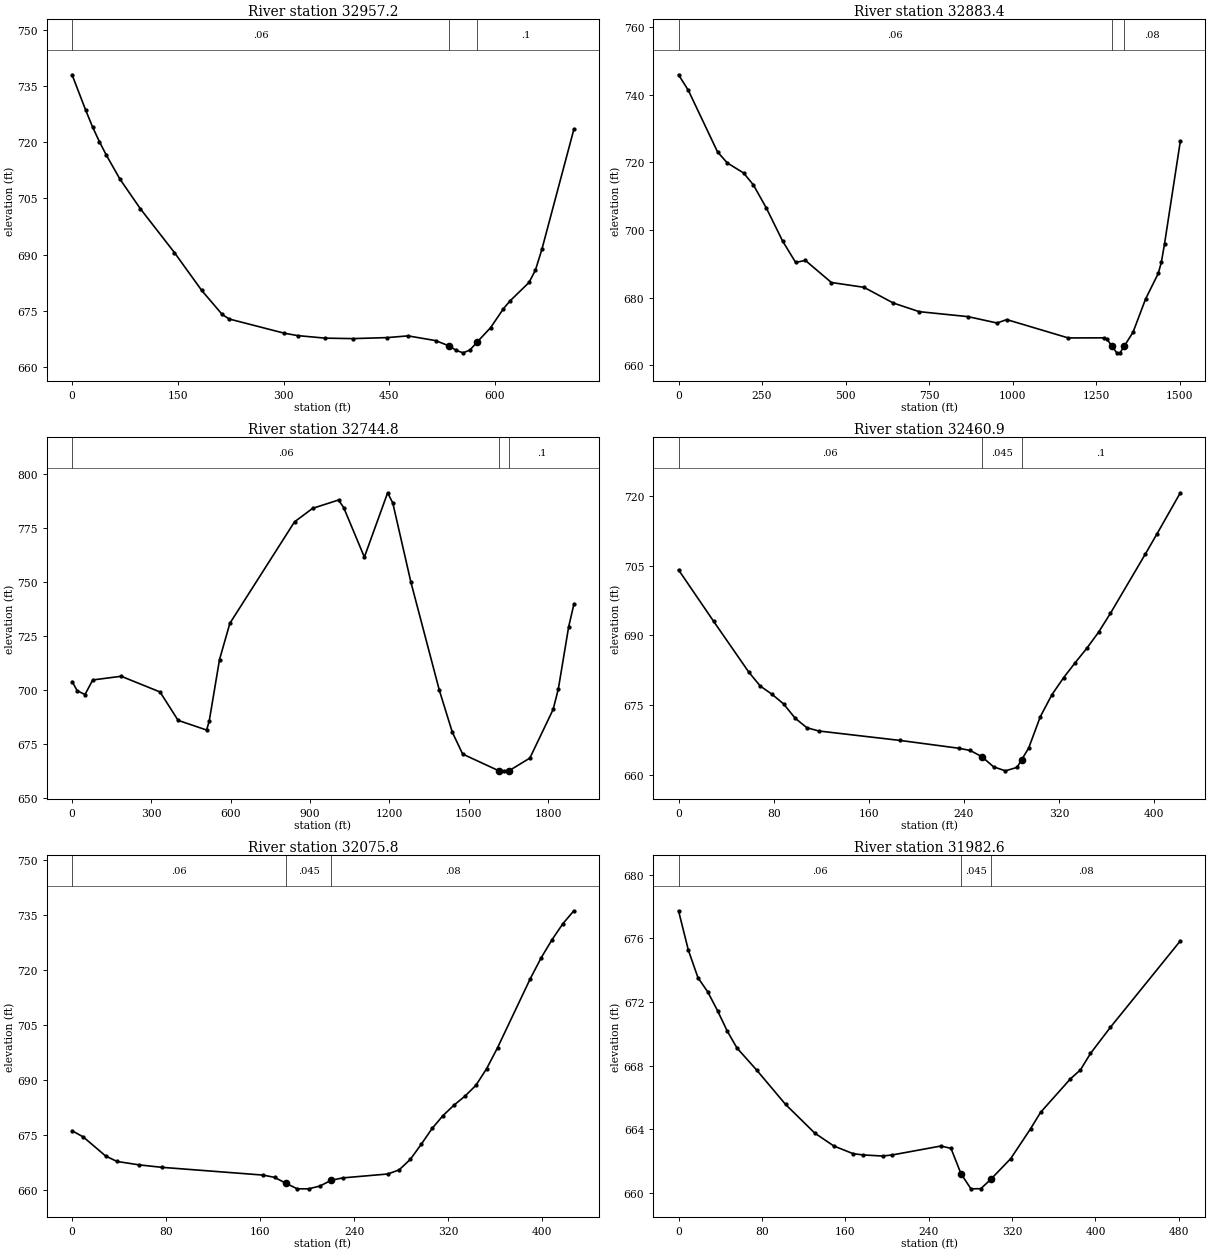
Type RM Length L Ch R = 1 ,32957.2 ,79.4,73.9,67.4
XS GIS Cut Line= 4
     1761566.381      573291.246     1761559.437      573088.121
     1761364.993      572749.579     1761248.673      572728.746
#Sta/Elev= 30
       0  738.02    19.4  728.54      29  724.12    38.7  720.19    48.4  716.64
    67.8   710.2    96.8  702.27   145.2  690.55   183.9  680.44     213  674.02
   222.8  672.82   300.8  669.03   320.4  668.37   359.4   667.7   398.4  667.58
   447.2  667.85   476.5  668.31   515.6  667.05   535.1  665.61   544.8  664.45
   554.6  663.78   564.4  664.53   574.1  666.56   593.6  670.48   611.8  675.53
   620.9  677.58   648.2  682.57   657.3  685.87   666.4  691.39   711.8  723.45
#Mann= 3 , 0 , 0
       0     .06       0   535.1    .045       0   574.1      .1       0
Bank Sta=535.1,574.1
XS Rating Curve= 0 ,0
Exp/Cntr=0.3,0.1

Type RM Length L Ch R = 1 ,32883.4 ,157.1,138.5,120.8
XS GIS Cut Line= 4
     1762238.875      573747.225     1761763.397      573069.954
     1761385.826      572694.024     1761245.201      572676.663
#Sta/Elev= 30
       0  745.96    29.2  741.38   116.8  723.12     146  719.86   194.7  716.89
   223.9  713.39   262.9   706.5   311.5  696.75   350.5  690.42   379.7     691
   457.6  684.47   554.9  683.05   642.5  678.41   720.4  675.84   866.3  674.37
   953.4  672.48   982.5  673.49  1166.6  668.06  1273.1  668.09  1282.8  667.67
 1297.24  665.61  1311.9  663.65  1321.6  663.66  1333.5  665.54  1360.3  669.72
  1398.1  679.61  1435.9  687.15  1445.3  690.49  1454.8  695.97    1502   726.3
#Mann= 3 , 0 , 0
       0     .06       0 1297.24    .045       0  1333.5     .08       0
Bank Sta=1297.24,1333.5
XS Rating Curve= 0 ,0
Exp/Cntr=0.3,0.1

Type RM Length L Ch R = 1 ,32744.8 ,284.5,283.9,283
XS GIS Cut Line= 3
     1762631.236      573590.975     1761925.908      572628.555
     1761222.631      572595.065
#Sta/Elev= 30
       0   703.8    19.6  699.54    48.9   697.8    78.2  704.54   185.8  706.24
   332.5  698.99     401  685.85   508.6  681.38   518.4  685.38   557.5  713.96
   596.6  730.73   841.1  777.68   909.6  783.92  1007.4  787.77  1026.9   784.3
  1105.2  761.36  1193.2  791.12  1212.8  786.34  1281.2  749.73  1388.8  699.71
  1437.7  680.38  1476.8  670.26  1613.7  662.52  1633.2   662.5  1653.7  662.65
    1731  668.41    1819  690.92  1838.6   700.4  1877.7  729.17  1897.3  739.49
#Mann= 3 , 0 , 0
       0     .06       0  1613.7    .045       0  1653.7      .1       0
Bank Sta=1613.7,1653.7
XS Rating Curve= 0 ,0
Exp/Cntr=0.3,0.1

Type RM Length L Ch R = 1 ,32460.9 ,392.2,385.2,378
XS GIS Cut Line= 2
     1761689.428      572371.758     1761267.553      572364.814
#Sta/Elev= 28
       0  704.11    29.4  693.07    58.9  682.16    68.7   679.1    78.5  677.35
    88.3  675.26    98.1  672.17   107.9  670.13   117.8  669.43   186.4  667.39
   235.5  665.72   245.3  665.23   255.1  663.88   264.9  661.71   274.8  660.85
   284.6  661.59   288.4  663.21   294.4  665.76   304.2  672.52     314  677.27
   323.8  680.91   333.6  684.16   343.4  687.27   353.2  690.71   363.1  694.74
   392.5  707.52   402.3  711.86   421.9   720.7
#Mann= 3 , 0 , 0
       0     .06       0   255.1    .045       0   288.4      .1       0
Bank Sta=255.1,288.4
XS Rating Curve= 0 ,0
Exp/Cntr=0.3,0.1

Type RM Length L Ch R = 1 ,32075.8 ,94.1,93.2,91.8
XS GIS Cut Line= 4
     1761610.088      571993.242     1761499.411      571963.946
     1761333.395      572013.859     1761218.378      572091.984
#Sta/Elev= 30
       0  676.11     9.5  674.42    28.6  669.21    38.2  667.73    57.2  666.79
    76.3  666.13   162.6  664.01   172.3  663.38   181.9  661.79   191.5  660.27
   201.2  660.26   210.8  661.02   220.4  662.58   230.1  663.24   268.6  664.31
   278.2  665.42   287.8  668.31   297.1  672.43   306.4  676.77   315.6  680.25
   324.9  683.08   334.2  685.53   343.5  688.46   352.7  693.04     362  698.77
   389.8  717.56   399.1  723.28   408.4  728.25   417.6   732.6   426.9   736.1
#Mann= 3 , 0 , 0
       0     .06       0   181.9    .045       0   220.4     .08       0
Bank Sta=181.9,220.4
XS Rating Curve= 0 ,0
Exp/Cntr=0.3,0.1

Type RM Length L Ch R = 1 ,31982.6 ,78.5,78.2,78.3
XS GIS Cut Line= 6
     1761637.519      571947.105     1761576.321      571904.136
     1761525.539      571880.699     1761489.081      571876.793
     1761317.206      571927.574     1761183.091      571928.876
#Sta/Elev= 29
       0  677.73     9.4  675.26    18.7  673.52      28  672.64    37.4  671.46
    46.7  670.18    56.1  669.11    74.8  667.74   102.7  665.57   130.7  663.77
     149  662.96   167.4  662.48   176.8   662.4   195.8  662.33   205.2   662.4
   251.8  662.96   261.4  662.81   270.9  661.23   280.5  660.27     290  660.28
   299.6  660.87   318.7  662.17   337.8  664.05   347.3  665.07     376  667.18
   385.6  667.74   395.2  668.77   414.4  670.42   481.4  675.84
#Mann= 3 , 0 , 0
       0     .06       0   270.9    .045       0   299.6     .08       0
Bank Sta=270.9,299.6
XS Rating Curve= 0 ,0
Exp/Cntr=0.3,0.1

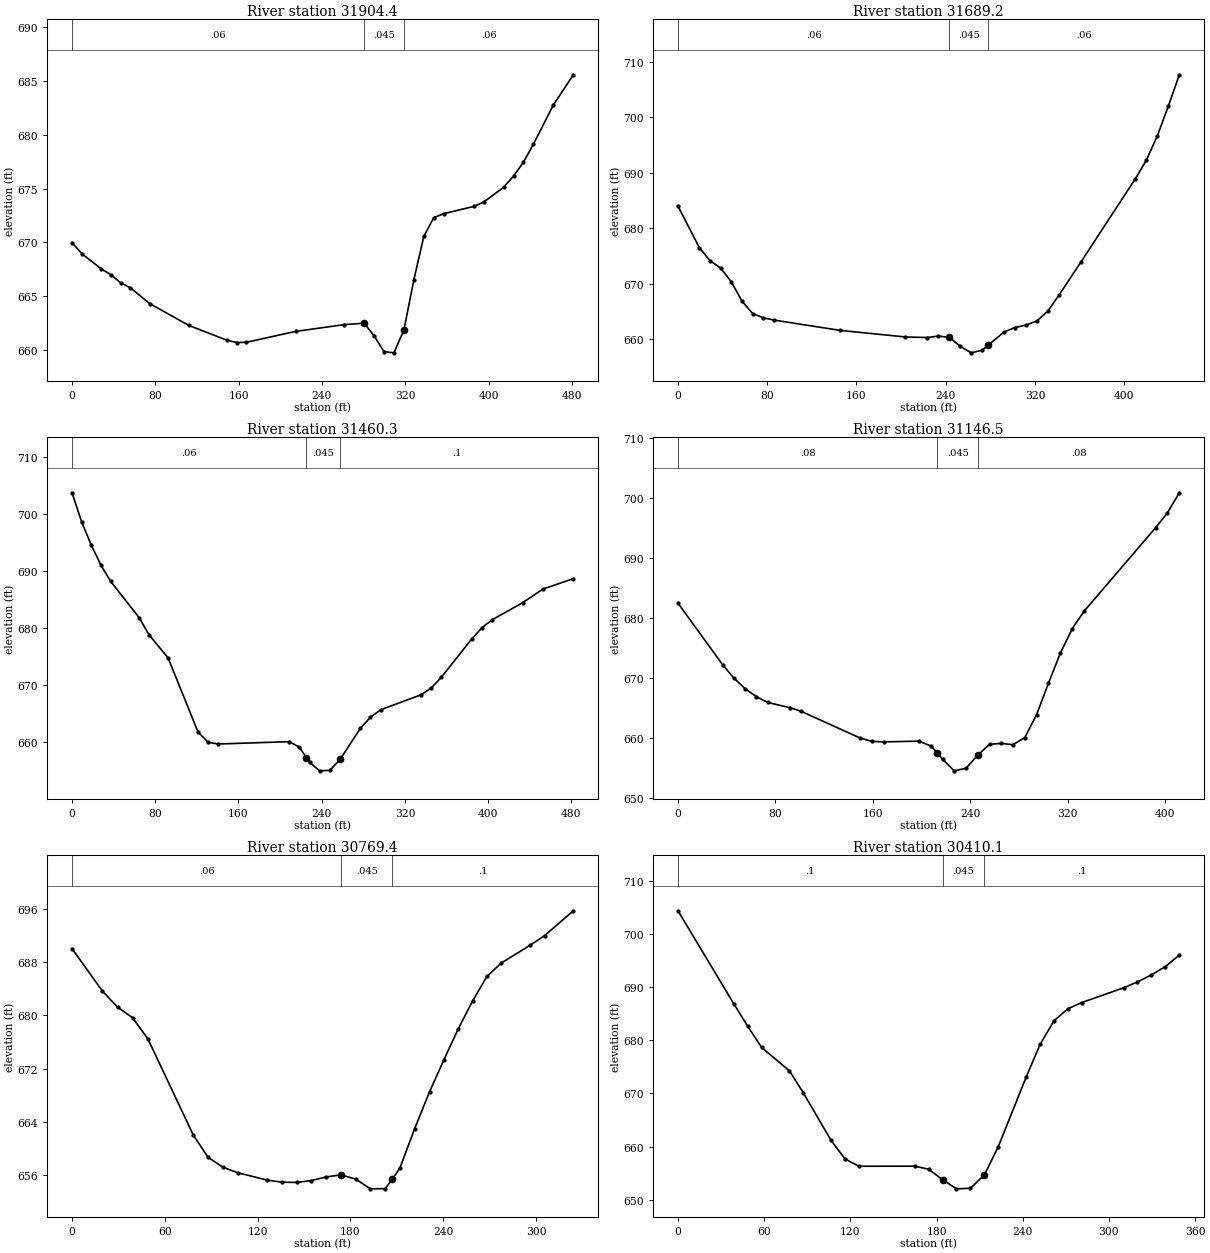
Type RM Length L Ch R = 1 ,31904.4 ,197.5,215.2,232.1
XS GIS Cut Line= 6
     1761634.914      571865.508     1761573.716      571822.539
     1761522.935      571799.102     1761486.477      571795.196
     1761314.602      571845.977     1761180.487      571847.279
#Sta/Elev= 30
       0  669.98     9.4  668.96      28  667.55    37.4     667    46.7  666.25
    56.1  665.78    74.8  664.31   112.1   662.3     149  660.91   158.2  660.71
   167.4  660.73   214.7  661.74   261.4  662.37   280.5   662.5     290  661.34
   299.6  659.86   309.1  659.75   318.7  661.88   328.2  666.51   337.8  670.56
   347.3   672.3   356.9  672.67   385.6  673.34   395.2  673.74   414.4  675.12
     424  676.17   433.5  677.46   443.1  679.13   462.3  682.78   481.4  685.57
#Mann= 3 , 0 , 0
       0     .06       0   280.5    .045       0   318.7     .06       0
Bank Sta=280.5,318.7
XS Rating Curve= 0 ,0
Exp/Cntr=0.3,0.1

Type RM Length L Ch R = 1 ,31689.2 ,237.2,229,220.3
XS GIS Cut Line= 3
     1761707.744      571774.058     1761626.364      571745.847
     1761296.503      571593.937
#Sta/Elev= 30
       0  683.97    19.1   676.5    28.7  674.12    38.3  672.78    47.8  670.31
    57.4  666.82      67  664.57    76.6  663.81    86.1  663.41     145  661.56
   203.9  660.36   223.5  660.26   233.4  660.52   243.2   660.3     253  658.68
   262.8   657.5   272.6  657.97   277.9  658.86   292.2  661.26   302.1  662.07
   311.9  662.51   321.7  663.26   331.5  665.03   341.3  667.86     361  673.84
     410  688.92   419.8  692.26   429.7  696.68   439.5  702.01   449.3  707.66
#Mann= 3 , 0 , 0
       0     .06       0   243.2    .045       0   277.9     .06       0
Bank Sta=243.2,277.9
XS Rating Curve= 0 ,0
Exp/Cntr=0.3,0.1

Type RM Length L Ch R = 1 ,31460.3 ,315.4,313.7,311.7
XS GIS Cut Line= 3
      1761790.21      571507.131     1761694.723      571472.409
     1761314.949      571452.878
#Sta/Elev= 30
       0  703.78     9.2  698.68    18.5  694.58    27.7  691.12      37  688.26
    64.7  681.83    73.9  678.89    92.4  674.78   121.1   661.8   130.9  659.99
   140.6   659.7   208.9  660.11   218.6  659.13  225.33   657.3   228.4  656.48
   238.1  654.99   247.9  655.08   257.6  656.98   277.1  662.44   286.9   664.4
   296.6   665.7   335.6  668.34   345.4  669.54   355.1  671.43   384.4  678.17
   394.1  680.11   403.9   681.5   433.1  684.48   452.6  686.88   481.9  688.71
#Mann= 3 , 0 , 0
       0     .06       0  225.33    .045       0   257.6      .1       0
Bank Sta=225.33,257.6
XS Rating Curve= 0 ,0
Exp/Cntr=0.3,0.1

Type RM Length L Ch R = 1 ,31146.5 ,383.6,377.1,370.3
XS GIS Cut Line= 4
     1761789.124      571129.527     1761695.808       571168.59
     1761502.521      571165.841     1761386.202      571151.952
#Sta/Elev= 30
       0  682.49    36.8  672.21      46     670    55.2  668.23    64.4  666.93
    73.6  665.95      92  665.09   101.2  664.47   149.5  660.04   159.2  659.48
   168.8  659.39   197.8  659.52   207.5  658.73  213.02  657.58   217.2   656.5
   226.8  654.57   236.5     655   246.1  657.18   255.8  658.99   265.5  659.14
   275.1  658.92   284.8  660.12   294.5  663.95   304.2  669.18     314  674.19
   323.8  678.27   333.5  681.16   392.1  695.04   401.8  697.51   411.6  700.87
#Mann= 3 , 0 , 0
       0     .08       0  213.02    .045       0   246.1     .08       0
Bank Sta=213.02,246.1
XS Rating Curve= 0 ,0
Exp/Cntr=0.3,0.1

Type RM Length L Ch R = 1 ,30769.4 ,354.6,359.3,364
XS GIS Cut Line= 4
     1761702.319      570769.284     1761624.194      570763.859
      1761477.71      570807.261     1761398.499       570856.09
#Sta/Elev= 30
       0  689.99    19.6  683.63    29.4  681.23    39.2  679.61      49  676.48
    78.3  662.09    87.9  658.73    97.4  657.24     107  656.41   126.1   655.3
   135.6  654.99   145.2  654.95   154.7  655.23   164.2  655.77   173.8  656.08
   183.4  655.45   192.9  653.99   202.4  654.02  207.09  655.42     212  657.15
   221.5  663.01   231.1  668.51   240.4  673.32   249.7  677.97     259  682.17
   268.3  685.84   277.6  687.85   296.2   690.5   305.5  691.94   324.1  695.66
#Mann= 3 , 0 , 0
       0     .06       0   173.8    .045       0  207.09      .1       0
Bank Sta=173.8,207.09
XS Rating Curve= 0 ,0
Exp/Cntr=0.3,0.1

Type RM Length L Ch R = 1 ,30410.1 ,466.7,462,456.9
XS GIS Cut Line= 2
     1761759.466      570450.563     1761410.508      570457.507
#Sta/Elev= 26
       0  704.35    38.8  686.89    48.5  682.65    58.2  678.65    77.6  674.25
    87.3  670.09   106.6  661.17   116.3  657.68     126  656.31   164.8  656.32
   174.5  655.75   184.2  653.78   193.9  652.06   203.6  652.17   213.3  654.67
     223     660   242.4  673.08   252.1  679.23   261.8  683.68   271.5  685.93
   281.2   687.1   310.2  689.86   319.9  690.97   329.6   692.3   339.3  693.85
     349  696.02
#Mann= 3 , 0 , 0
       0      .1       0   184.2    .045       0   213.3      .1       0
Bank Sta=184.2,213.3
XS Rating Curve= 0 ,0
Exp/Cntr=0.3,0.1

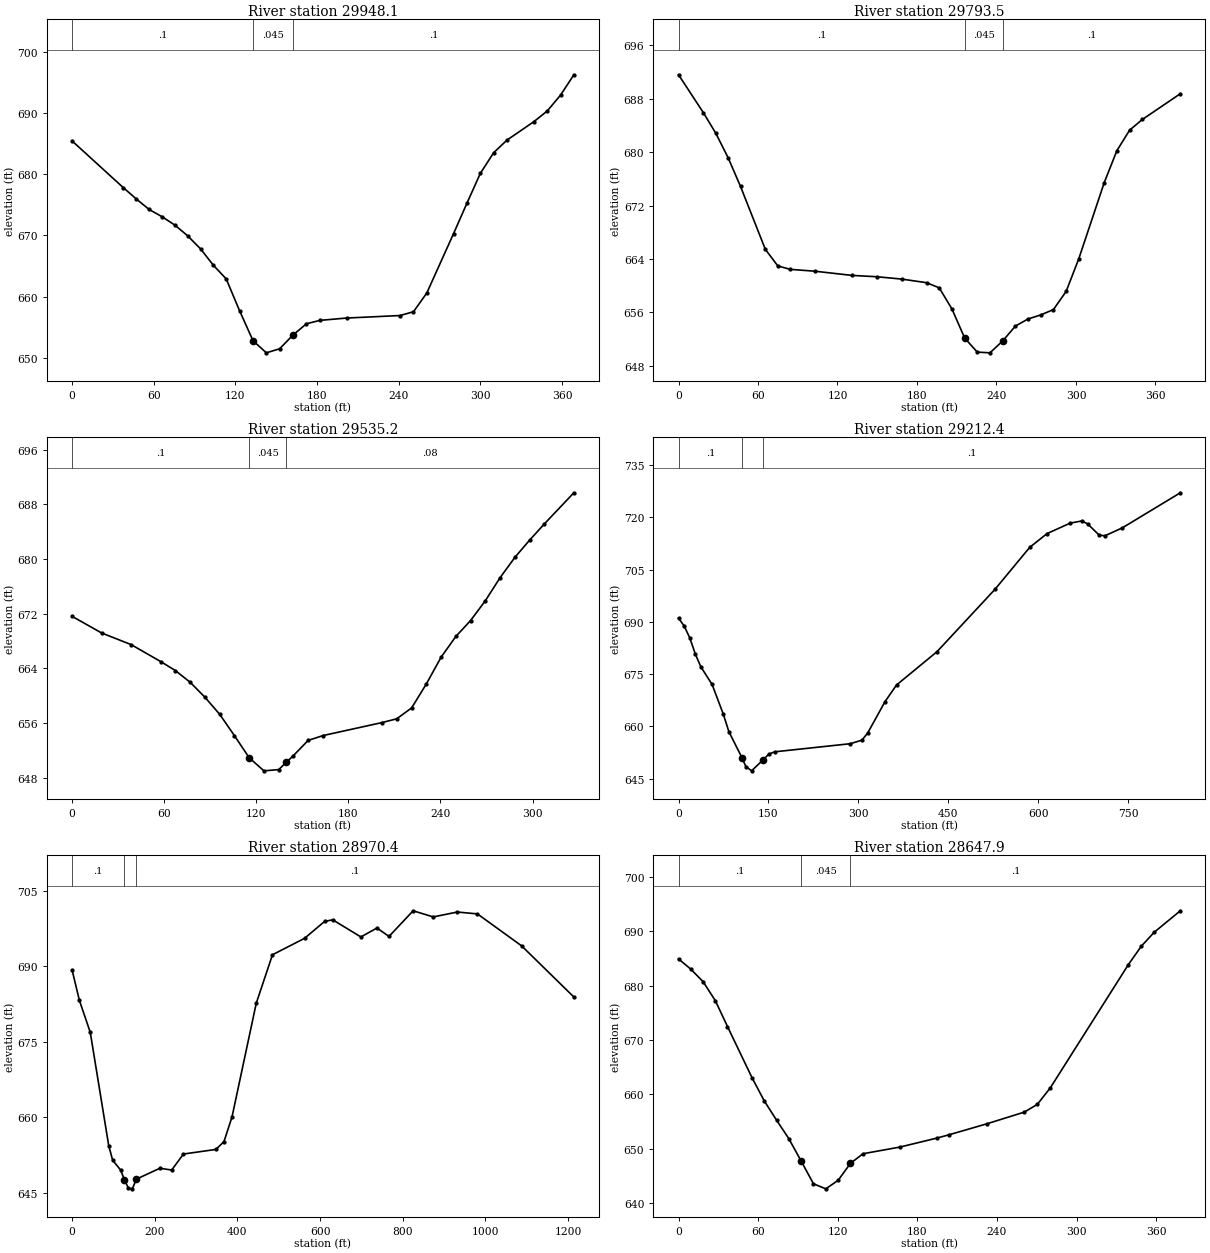
Type RM Length L Ch R = 1 ,29948.1 ,151.8,154.6,156.5
XS GIS Cut Line= 3
     1761698.702      570075.563     1761606.688      570009.591
     1761361.896      570082.507
#Sta/Elev= 30
       0  685.42    37.7  677.78    47.2  675.94    56.6  674.23      66  673.06
    75.5  671.68    84.9  669.93    94.4  667.79   103.8  665.12   113.2   662.9
     123  657.72   132.9  652.81   142.7  650.82   152.5  651.49   162.3  653.73
   172.2  655.57     182  656.12   201.6   656.5   240.9  656.91   250.8  657.53
   260.6   660.6   280.2  670.27     290  675.22   299.9  680.12   309.7   683.5
   319.5  685.56   339.2  688.56     349   690.3   358.8  692.89   368.6  696.22
#Mann= 3 , 0 , 0
       0      .1       0   132.9    .045       0   162.3      .1       0
Bank Sta=132.9,162.3
XS Rating Curve= 0 ,0
Exp/Cntr=0.3,0.1

Type RM Length L Ch R = 1 ,29793.5 ,262.9,258.3,253.4
XS GIS Cut Line= 3
     1761712.591      569799.521     1761542.452      569877.646
     1761356.688      569924.521
#Sta/Elev= 30
       0   691.6    18.7  685.94    28.1  682.85    37.4  679.18    46.8  674.87
    65.5  665.46    74.9  662.97    84.2  662.45     103  662.17     131  661.54
   149.8  661.34   168.5  660.99   187.2  660.45   196.8  659.68   206.4  656.51
     216  652.16   225.5  650.05   235.1  649.94   244.7  651.72   254.3  653.95
   263.8  655.01   273.4  655.62     283  656.42   292.6  659.14   302.2  664.06
   321.3  675.41   330.9  680.23   340.5   683.3   350.1   684.9   378.8  688.76
#Mann= 3 , 0 , 0
       0      .1       0     216    .045       0   244.7      .1       0
Bank Sta=216,244.7
XS Rating Curve= 0 ,0
Exp/Cntr=0.3,0.1

Type RM Length L Ch R = 1 ,29535.2 ,318.3,322.9,325.8
XS GIS Cut Line= 2
     1761627.521      569610.285     1761325.438      569735.285
#Sta/Elev= 29
       0   671.6    19.2  669.17    38.5  667.46    57.7  664.99    67.3  663.67
    76.9  661.96    86.5  659.78    96.2  657.26   105.8  654.14   115.4  650.91
     125     649   134.6  649.18   139.6  650.25   144.2  651.23   153.8  653.45
   163.5  654.16   201.9  656.06   211.5  656.61   221.2   658.2   230.8  661.71
   240.4  665.62     250  668.65   259.6  670.98   269.2  673.87   278.8  677.24
   288.5  680.23   298.1  682.75   307.7  685.12   326.9  689.67
#Mann= 3 , 0 , 0
       0      .1       0   115.4    .045       0   139.6     .08       0
Bank Sta=115.4,139.6
XS Rating Curve= 0 ,0
Exp/Cntr=0.3,0.1

Type RM Length L Ch R = 1 ,29212.4 ,224.1,242,259.4
XS GIS Cut Line= 6
     1761620.577      569353.341     1761518.146      569346.396
     1761452.174      569360.285      1761328.91      569417.577
     1761263.934      569535.833     1760982.075      569814.499
#Sta/Elev= 30
       0  691.09     9.3  688.86    18.7  685.44      28  680.77    37.3  677.08
      56  672.04    74.7  663.51      84  658.49  106.07  650.92   112.3  648.47
   121.9  647.23   141.2  650.41   150.8  652.04   160.4  652.69   286.6  655.02
     306  656.05   315.6  658.08   344.6  667.12   363.8  671.89   431.3  681.45
     528  699.35     586  711.41     615  715.37   653.6  718.37     673  718.99
   682.6  718.15     702   714.9   711.6  714.74   740.6  717.01   837.3  727.08
#Mann= 3 , 0 , 0
       0      .1       0  106.07    .045       0   141.2      .1       0
Bank Sta=106.07,141.2
XS Rating Curve= 0 ,0
Exp/Cntr=0.3,0.1

Type RM Length L Ch R = 1 ,28970.4 ,333.4,322.5,308.8
XS GIS Cut Line= 5
     1761622.313      569216.188     1761552.869      569177.994
      1761391.41      569077.299      1761195.23      568988.757
     1760699.957        569523.7
#Sta/Elev= 30
       0  689.29    17.6  683.25      44  676.87    88.8  654.28    98.3  651.43
   117.3  649.52   126.8  647.53   136.3   645.9   145.8  645.76   155.4  647.68
   212.4  649.85     241   649.5   269.5  652.68   347.8  653.59   367.4  655.14
   386.9  660.05   445.6  682.67   484.8  692.29   562.5  695.56   611.1  698.93
   630.6  699.23   698.6  695.83   737.5   697.6   766.7  695.93     825  701.03
   873.6  699.81   931.9  700.78   980.5  700.41  1087.4  694.06  1213.8  683.89
#Mann= 3 , 0 , 0
       0      .1       0   126.8    .045       0   155.4      .1       0
Bank Sta=126.8,155.4
XS Rating Curve= 0 ,0
Exp/Cntr=0.3,0.1

Type RM Length L Ch R = 1 ,28647.9 ,191.3,196.7,201
XS GIS Cut Line= 4
     1761639.457      568866.796     1761552.652      568835.329
     1761394.232      568840.754     1761277.044      568790.841
#Sta/Elev= 26
       0  684.89     9.2  683.02    18.5  680.71    27.7  677.24    36.9  672.46
    55.4  663.05    64.6   658.8    73.9  655.25    83.1  651.86    92.3  647.79
   101.7  643.56     111  642.63   120.3   644.2   129.6  647.32     139  649.08
   166.9  650.31   194.9  651.97   204.2  652.59   232.2  654.57   260.6  656.73
   270.4  658.15   280.2  661.19     339  683.83   348.8  687.23   358.6  689.81
   378.2  693.74
#Mann= 3 , 0 , 0
       0      .1       0    92.3    .045       0   129.6      .1       0
Bank Sta=92.3,129.6
XS Rating Curve= 0 ,0
Exp/Cntr=0.3,0.1

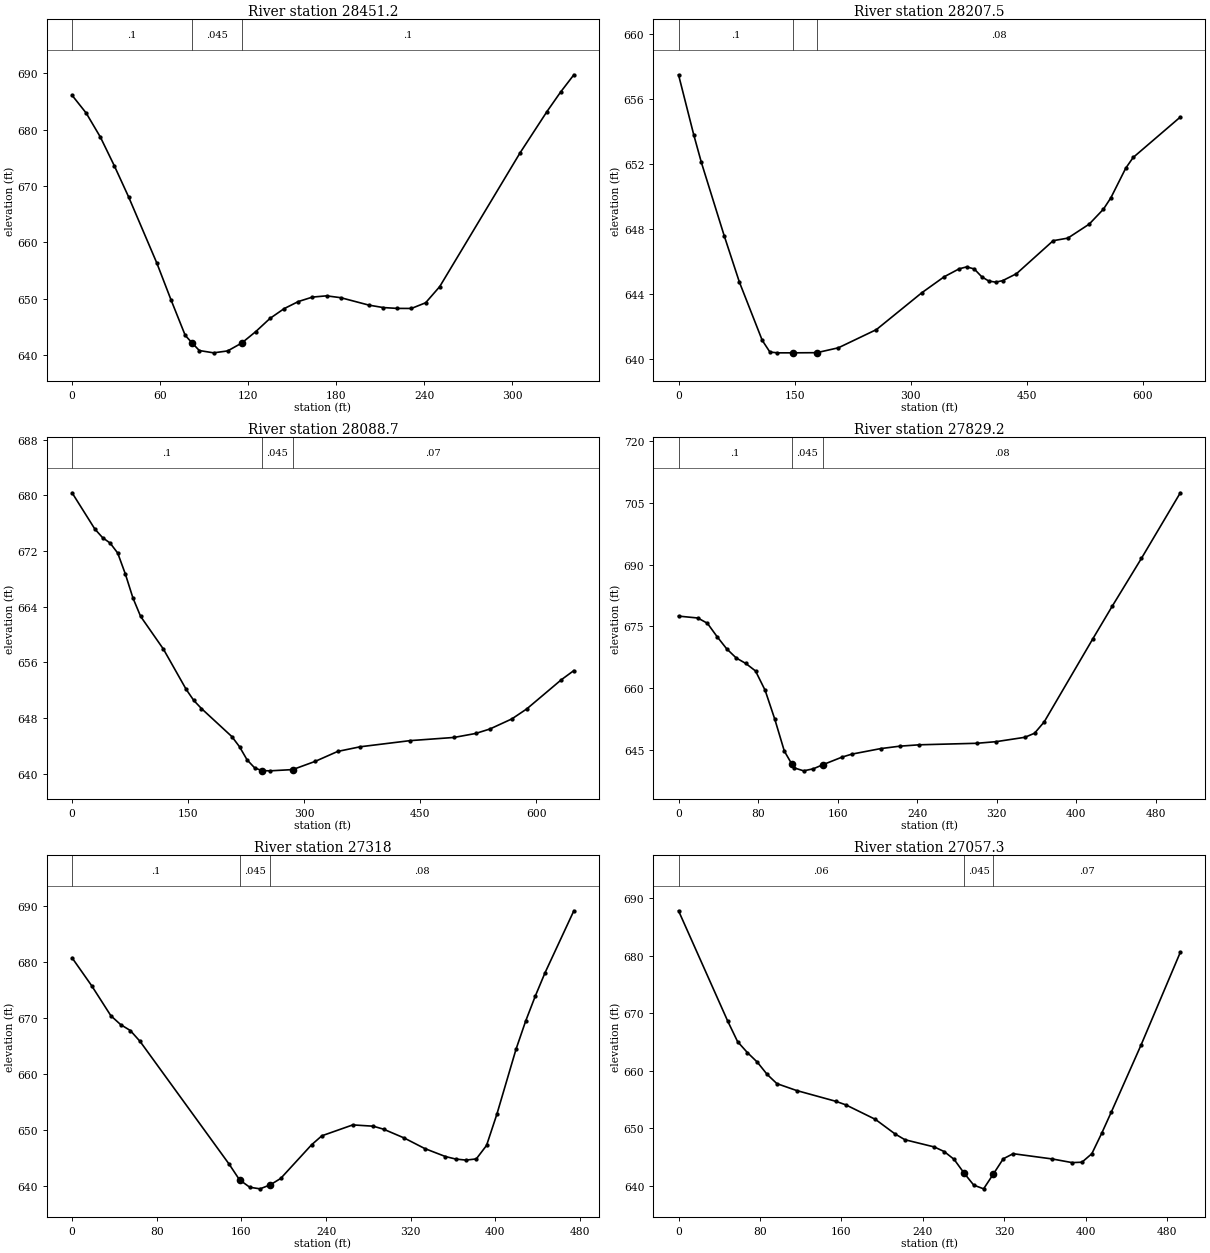
Type RM Length L Ch R = 1 ,28451.2 ,169.7,243.6,285.7
XS GIS Cut Line= 3
     1761688.285      568706.205      1761451.74       568623.74
      1761372.53      568578.167
#Sta/Elev= 30
       0  686.13     9.6  682.98    19.3   678.7    28.9  673.55    38.5   668.1
    57.8  656.31    67.4  649.82    77.1   643.5   81.53  642.23    86.7  640.81
    96.4   640.4     106  640.74   115.6  642.14   125.2  644.18   134.9  646.52
   144.5  648.25   154.2  649.51   163.8   650.3   173.4  650.52   183.1  650.19
   202.3  648.87     212  648.44   221.6  648.29   231.2  648.28   240.9  649.29
   250.5  652.16   305.3  675.93   323.6  683.25   332.8  686.68   341.9  689.77
#Mann= 3 , 0 , 0
       0      .1       0   81.53    .045       0   115.6      .1       0
Bank Sta=81.53,115.6
XS Rating Curve= 0 ,0
Exp/Cntr=0.3,0.1

Type RM Length L Ch R = 1 ,28207.5 ,160.3,118.8,109.6
XS GIS Cut Line= 6
     1761651.393      568605.511     1761587.591      568218.792
     1761565.455       568179.73     1761506.862       568148.48
     1761461.289      568141.969     1761371.445      568100.303
#Sta/Elev= 30
       0  657.51    19.7  653.81    29.5  652.12      59  647.61    78.7  644.75
   108.2  641.17   118.1  640.45   127.9   640.4   147.6   640.4   178.8  640.41
   206.6  640.71   255.8  641.83   314.3  644.09   343.4  645.08   362.8  645.57
   372.6  645.69   382.3  645.56     392  645.08     401  644.82   409.9  644.75
   418.9  644.84   436.9  645.27   484.3   647.3   503.3  647.46   530.9  648.32
   549.3  649.24   558.9  649.94   578.1  651.76   587.7  652.42   648.7  654.91
#Mann= 3 , 0 , 0
       0      .1       0   147.6    .045       0   178.8     .08       0
Bank Sta=147.6,178.8
XS Rating Curve= 0 ,0
Exp/Cntr=0.3,0.1

Type RM Length L Ch R = 1 ,28088.7 ,282.2,259.5,239
XS GIS Cut Line= 6
     1761715.195      568579.469     1761651.393       568192.75
     1761629.258      568153.688     1761570.664      568122.438
     1761525.091      568115.928     1761435.247      568074.261
#Sta/Elev= 30
       0  680.36    29.5  675.14    39.4  673.92    49.2  673.13      59   671.7
    68.9  668.68    78.7  665.24    88.6   662.6   118.1  657.89   147.6  652.09
   157.4  650.51   167.3  649.35   206.6  645.32   216.5  643.86   226.3  641.97
   236.2  640.81   245.6  640.43   255.8   640.4   285.2  640.58   314.3  641.76
   343.4  643.19   372.6  643.86   436.9  644.74   493.8   645.2   521.7  645.77
   540.1  646.41   568.5  647.86   587.7  649.29   632.6   653.5   648.7  654.81
#Mann= 3 , 0 , 0
       0      .1       0   245.6    .045       0   285.2     .07       0
Bank Sta=245.6,285.2
XS Rating Curve= 0 ,0
Exp/Cntr=0.3,0.1

Type RM Length L Ch R = 1 ,27829.2 ,512.3,511.2,505.6
XS GIS Cut Line= 3
     1761901.827      568187.976     1761624.049      567947.091
     1761558.945      567826.648
#Sta/Elev= 30
       0  677.51    19.4  677.05      29  675.78    38.7  672.56    48.4   669.6
      58  667.38    67.7  666.04    77.4  664.24    87.1  659.54    96.8  652.55
   106.4  644.83   113.6  641.83   116.1  640.79   125.8  640.06   135.5  640.55
   145.1  641.54   164.5  643.39   174.2   644.1   203.2  645.44   222.5  646.03
   241.9  646.36     300  646.73   319.3  647.12   348.3  648.18     358  649.16
   367.7   651.9   416.6  672.01   436.1   679.9   465.5  691.49   504.6  707.36
#Mann= 3 , 0 , 0
       0      .1       0   113.6    .045       0   145.1     .08       0
Bank Sta=113.6,145.1
XS Rating Curve= 0 ,0
Exp/Cntr=0.3,0.1

Type RM Length L Ch R = 1 ,27318   ,260.1,260.7,263.2
XS GIS Cut Line= 4
     1762187.851      567872.438     1762117.539      567776.084
     1761881.862      567621.136      1761831.08      567569.053
#Sta/Elev= 30
       0  680.74    18.4   675.8    36.7  670.41    45.9  668.84      55  667.79
    64.2  665.86   148.5  643.95   158.2  641.19   167.9  639.86   177.6  639.58
   187.4  640.31   197.1  641.43   226.3  647.43     236  649.03   265.2  650.97
   284.6  650.74   294.4   650.2   313.8  648.64   333.2  646.76   352.7  645.34
   362.4  644.89   372.2   644.7   381.9  644.91   391.6  647.31   401.3  652.84
   419.5  664.48   428.6  669.49   437.7  673.94   446.8  678.05   474.1  689.12
#Mann= 3 , 0 , 0
       0      .1       0   158.2    .045       0   187.4     .08       0
Bank Sta=158.2,187.4
XS Rating Curve= 0 ,0
Exp/Cntr=0.3,0.1

Type RM Length L Ch R = 1 ,27057.3 ,441.9,440.9,439.5
XS GIS Cut Line= 2
      1762324.57       567686.24     1761901.393      567433.636
#Sta/Elev= 30
       0  687.78    48.3   668.6      58  665.03    67.6  663.13    77.3  661.48
      87  659.34    96.6  657.73     116  656.53   154.6  654.65   164.3  654.04
   193.3  651.52   212.6  648.99   222.3  647.98   251.2  646.72   260.9  645.92
   270.6  644.57   280.2  642.23   289.9  640.09   299.6  639.44   309.2  642.02
   318.9  644.66   328.6  645.55   367.2  644.63   386.5     644   396.2  644.07
   405.9  645.55   415.5  649.07   425.2  652.86   454.2  664.43   492.8  680.57
#Mann= 3 , 0 , 0
       0     .06       0   280.2    .045       0   309.2     .07       0
Bank Sta=280.2,309.2
XS Rating Curve= 0 ,0
Exp/Cntr=0.3,0.1

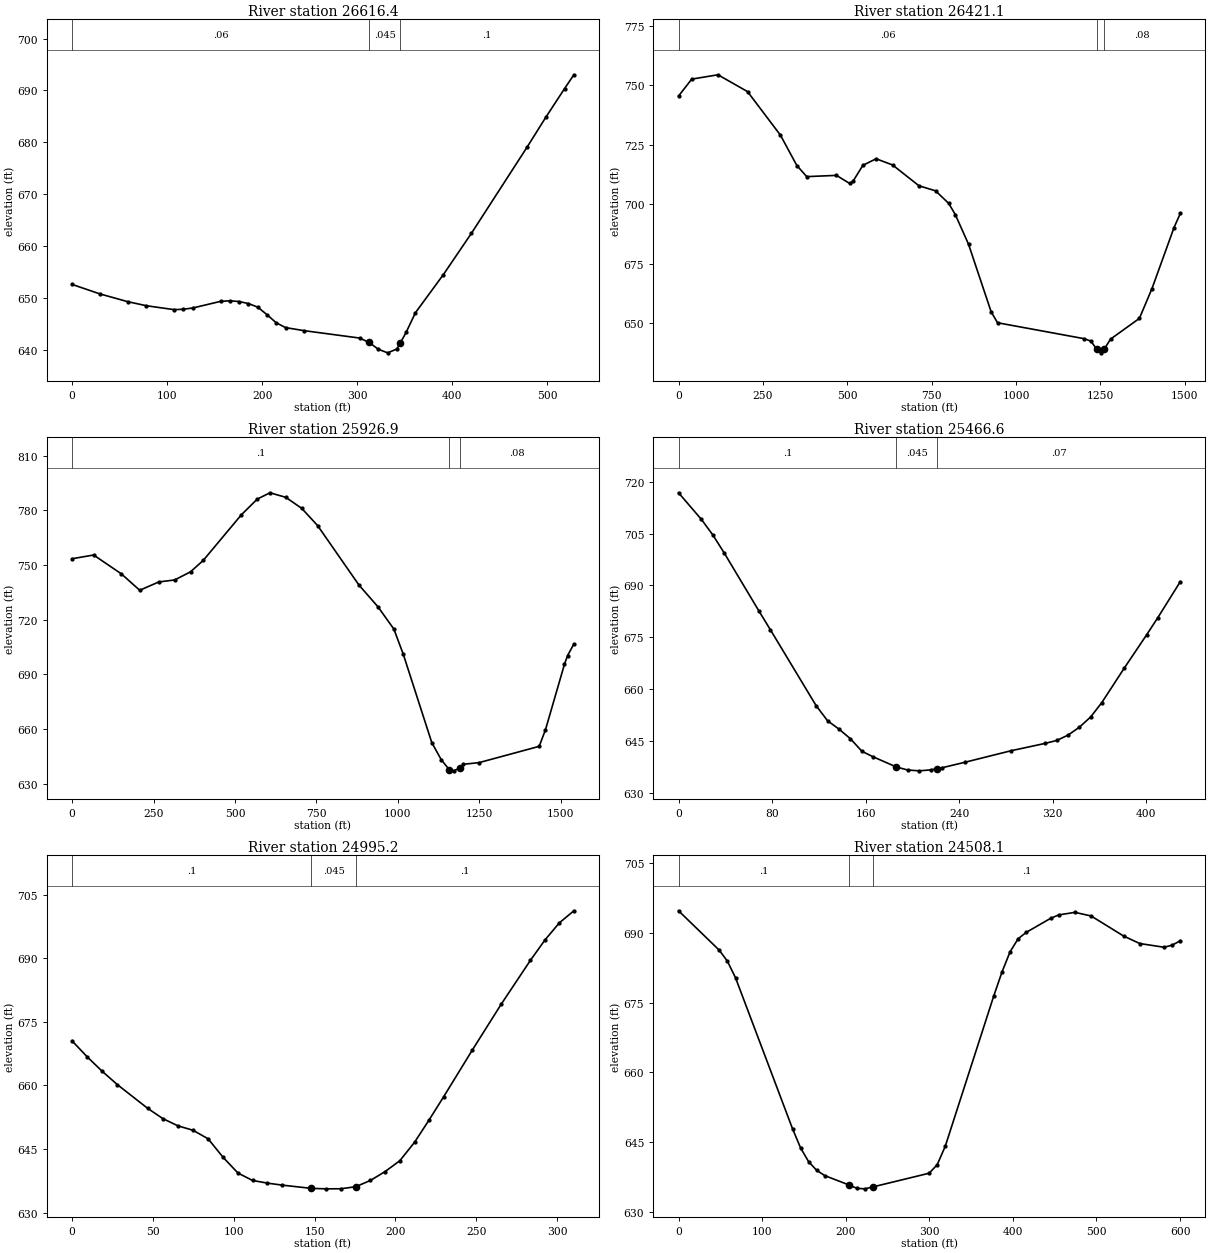
Type RM Length L Ch R = 1 ,26616.4 ,194.5,195.2,195.1
XS GIS Cut Line= 3
     1762426.133      567293.011     1762111.028      567115.928
     1761948.268      567152.386
#Sta/Elev= 30
       0  652.57    29.3  650.74    58.6  649.24    78.2  648.46   107.5   647.7
   117.2  647.78     127  648.02   156.3   649.3   166.1  649.41   175.8  649.27
   185.6  648.88   195.4  648.19   205.2  646.73   214.9  645.17   224.7  644.24
   244.2  643.65   302.8  642.22   312.6  641.38   322.4  640.06   332.2  639.37
   341.9  640.11  345.44  641.25   351.7  643.34   361.4   647.1   390.9  654.48
   420.3  662.41   479.2  679.12   498.8  684.85   518.4  690.34   528.2  693.01
#Mann= 3 , 0 , 0
       0     .06       0   312.6    .045       0  345.44      .1       0
Bank Sta=312.6,345.44
XS Rating Curve= 0 ,0
Exp/Cntr=0.3,0.1

Type RM Length L Ch R = 1 ,26421.1 ,512.5,494.2,475.7
XS GIS Cut Line= 6
     1763230.339      567761.548     1763010.025      567452.234
     1762545.219      567245.429     1762436.549      567091.188
     1762219.101      566966.188     1762134.466      566832.073
#Sta/Elev= 30
       0  745.45      39  752.57   116.8   754.4   204.5  747.32   301.9  729.01
   350.5  716.25   379.8  711.57   467.8   712.1   506.9  708.71   516.7  709.58
   546.1  716.31   585.2  719.09   634.1  716.48   712.4  707.71   761.3  705.62
   800.4  700.32     820   695.6   859.1  683.16   926.2  654.71   945.1  650.13
  1202.6  643.41  1221.9  642.38 1238.78  639.02  1250.8  637.48  1260.5  638.89
  1279.8  643.24  1365.3  651.96  1402.6  664.48  1467.9  690.14  1486.6  696.12
#Mann= 3 , 0 , 0
       0     .06       0 1238.78    .045       0  1260.5     .08       0
Bank Sta=1238.78,1260.5
XS Rating Curve= 0 ,0
Exp/Cntr=0.3,0.1

Type RM Length L Ch R = 1 ,25926.9 ,443,460.3,477.2
XS GIS Cut Line= 5
     1763529.818      566949.916      1763325.75       566988.76
      1762689.48      566537.329     1762341.931      566627.212
     1762148.789      566614.191
#Sta/Elev= 30
       0  753.49    66.1  755.54   151.1  745.22   207.7  736.19   266.2  740.76
     315  741.84   363.8  746.34   402.8   752.6   519.8  777.63   568.6  786.24
   607.6  789.69   656.3  787.18   705.1  781.12   753.8  771.69   880.6  739.07
   939.1  727.11   987.9  714.88    1017  700.95  1104.3  652.56  1133.4  643.18
  1158.6  637.58  1172.2   637.1  1191.6  638.85  1201.3  640.68  1249.8  641.63
    1434  650.54  1453.3  659.67  1511.4  695.49  1521.1  700.36  1540.4   706.7
#Mann= 3 , 0 , 0
       0      .1       0  1158.6    .045       0  1191.6     .08       0
Bank Sta=1158.6,1191.6
XS Rating Curve= 0 ,0
Exp/Cntr=0.3,0.1

Type RM Length L Ch R = 1 ,25466.6 ,473.4,471.4,468.3
XS GIS Cut Line= 3
     1762679.171      566242.664     1762382.296      566091.622
     1762304.171      566036.066
#Sta/Elev= 30
       0  716.76    19.6  709.05    29.4  704.55    39.2   699.3    68.6   682.7
    78.4  677.28   117.6  655.31   127.4  650.93   137.2  648.52     147  645.72
   156.8  642.11   166.5   640.5   186.1   637.6   195.9  636.71   205.7  636.47
   215.5  636.74   221.1  637.09   225.3  637.36   244.9  638.95   284.1  642.26
   313.5   644.4   323.3  645.24   333.1   646.8   342.7  649.07   352.3  652.01
   361.8  656.14     381   666.1   400.2  675.75   409.8  680.72     429  691.11
#Mann= 3 , 0 , 0
       0      .1       0   186.1    .045       0   221.1     .07       0
Bank Sta=186.1,221.1
XS Rating Curve= 0 ,0
Exp/Cntr=0.3,0.1

Type RM Length L Ch R = 1 ,24995.2 ,488.2,487.1,485.9
XS GIS Cut Line= 4
     1762717.365      565786.066     1762640.976      565732.247
     1762531.601      565687.108     1762436.115      565662.803
#Sta/Elev= 30
       0   670.5     9.3  666.75    18.7   663.3      28  660.18    46.7   654.6
    56.1  652.17    65.4  650.47    74.8  649.41    84.1  647.41    93.4  643.03
   102.6  639.32   111.6  637.58   120.8  636.95   129.8  636.48     148  635.71
   157.2   635.6   166.3  635.62   175.4   636.1   184.5  637.58   193.6  639.68
   202.7  642.24   211.8  646.59   220.7   651.8   229.7  657.27   247.6  668.39
   265.5  679.22   283.4  689.47   292.4  694.28   301.3  698.32   310.3  701.18
#Mann= 3 , 0 , 0
       0      .1       0     148    .045       0   175.4      .1       0
Bank Sta=148,175.4
XS Rating Curve= 0 ,0
Exp/Cntr=0.3,0.1

Type RM Length L Ch R = 1 ,24508.1 ,363.5,372.6,381.2
XS GIS Cut Line= 4
     1762878.824      565372.872     1762776.393      565268.705
     1762613.199      565211.414     1762331.949      565214.886
#Sta/Elev= 30
       0  694.74    48.7  686.26    58.4  683.91    68.2  680.31   136.4  647.82
   146.1  643.67   155.7  640.72   165.3  638.88   174.9  637.75   203.7  635.75
   213.4  635.01     223   634.9   232.6  635.32   299.8  638.26   309.4  640.08
     319  644.02   377.2  676.46   386.9  681.54   396.6   685.9   406.3  688.73
     416   690.1   445.1  693.11   454.8  693.85   474.2   694.4   493.6  693.62
   532.4  689.31   551.8  687.69   580.9  686.89   590.6  687.35   600.3  688.29
#Mann= 3 , 0 , 0
       0      .1       0   203.7    .045       0   232.6      .1       0
Bank Sta=203.7,232.6
XS Rating Curve= 0 ,0
Exp/Cntr=0.3,0.1

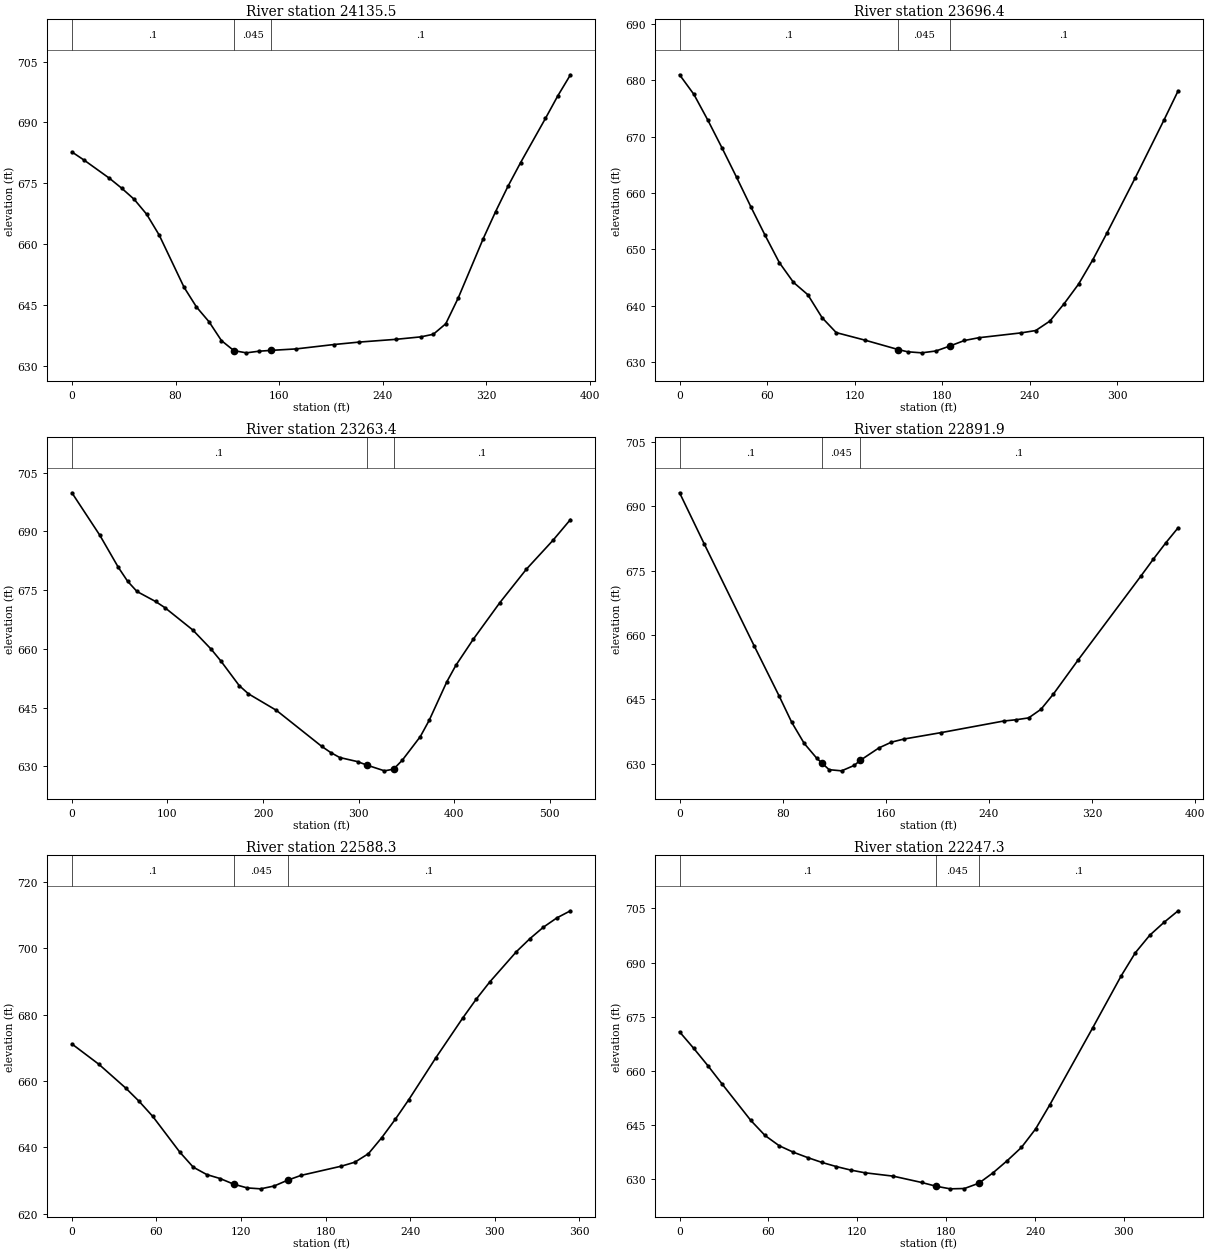
Type RM Length L Ch R = 1 ,24135.5 ,436.8,439.1,441.9
XS GIS Cut Line= 2
     1762903.129      564977.039     1762614.935       564721.83
#Sta/Elev= 30
       0  682.73     9.6  680.68    28.9  676.26    38.5  673.78    48.1  671.05
    57.7  667.38    67.4  662.24    86.6  649.37    96.2   644.5   105.9  640.86
   115.5  636.21   125.1  633.74   134.7   633.2   144.4   633.6     154  633.81
   173.2  634.17   202.1  635.24   221.4  635.84   250.2  636.53   269.5  637.14
   279.1  637.78   288.7  640.37   298.3  646.71   317.6  661.33   327.2  668.03
   336.8   674.3   346.5  680.11   365.7  691.01   375.3  696.61     385  701.76
#Mann= 3 , 0 , 0
       0      .1       0   125.1    .045       0     154      .1       0
Bank Sta=125.1,154
XS Rating Curve= 0 ,0
Exp/Cntr=0.3,0.1

Type RM Length L Ch R = 1 ,23696.4 ,431.6,433,432.5
XS GIS Cut Line= 2
      1763130.56      564641.969     1762903.129      564386.761
#Sta/Elev= 30
       0  680.96     9.8  677.49    19.5  672.85    29.3  667.88    39.1  662.76
    48.8  657.57    58.6  652.49    68.4  647.63    78.1  644.12    87.9  641.94
    97.7  637.86   107.4  635.21     127  633.88   149.8  632.21   156.3  631.81
     166  631.62   175.8  631.95   185.6  632.86   195.3  633.81   205.1   634.3
   234.4  635.17   244.2  635.58   253.9  637.26   263.7  640.36   273.5   643.8
   283.2  648.08     293  652.88   312.5  662.73   332.1  672.93   341.8  678.11
#Mann= 3 , 0 , 0
       0      .1       0   149.8    .045       0   185.6      .1       0
Bank Sta=149.8,185.6
XS Rating Curve= 0 ,0
Exp/Cntr=0.3,0.1

Type RM Length L Ch R = 1 ,23263.4 ,411.7,371.5,331.3
XS GIS Cut Line= 4
      1763576.74      564358.983     1763354.518      564287.803
      1763264.24      564180.164     1763120.143      564147.178
#Sta/Elev= 30
       0  699.87    29.2  689.03    48.6  680.82    58.3  677.28    68.1  674.67
    87.5  672.12    97.2  670.56   126.4  664.86   145.8  659.91   155.6  657.01
     175  650.66   184.7  648.55   213.9  644.34   261.4  635.13   270.8  633.56
   280.2  632.29   298.9  631.24   308.3  630.38     327  628.89   336.5  629.31
   345.7  631.62   364.5  637.63   373.8  641.79   392.3  651.65   401.6  655.78
     420  662.51   447.7  671.82   475.5  680.37   503.2  687.71   521.6  693.04
#Mann= 3 , 0 , 0
       0      .1       0   308.3    .045       0   336.5      .1       0
Bank Sta=308.3,336.5
XS Rating Curve= 0 ,0
Exp/Cntr=0.3,0.1

Type RM Length L Ch R = 1 ,22891.9 ,299.4,303.6,307.6
XS GIS Cut Line= 3
     1763417.018      563845.094      1763255.56      564037.803
      1763130.56      564089.886
#Sta/Elev= 26
       0  693.17    19.3  681.14      58  657.41    77.4   645.7      87  639.67
    96.7  634.74   106.4   631.3   110.2  630.24     116  628.62   125.7  628.35
   135.4   629.6   140.3  630.82   154.7   633.7   164.4  635.04     174  635.76
   203.1  637.27   251.4  639.96   261.1  640.26   270.8  640.69   280.4   642.7
   290.1  646.28   309.4  654.27   357.8  673.71   367.5  677.67   377.2  681.49
   386.8  685.02
#Mann= 3 , 0 , 0
       0      .1       0   110.2    .045       0   140.3      .1       0
Bank Sta=110.2,140.3
XS Rating Curve= 0 ,0
Exp/Cntr=0.3,0.1

Type RM Length L Ch R = 1 ,22588.3 ,313.8,341,368.8
XS GIS Cut Line= 3
     1763177.579      563718.763     1763113.343       563760.43
     1762901.538      563939.249
#Sta/Elev= 30
       0  671.19    19.1  665.08    38.3  657.86    47.8  653.86    57.4  649.35
    76.6  638.58    86.1  634.07    95.7  631.84   105.2  630.64   114.8  628.95
   124.4  627.82   133.9  627.54   143.5  628.39     153  630.13   162.6  631.59
   191.3  634.38   200.8  635.57   210.4  638.12   219.9  642.97   229.5   648.5
   239.1  654.42   258.2  666.98   277.3  678.97   286.8  684.61   296.4   689.8
   315.5  699.02   325.1  702.94   334.6  706.37   344.2  709.18   353.8  711.31
#Mann= 3 , 0 , 0
       0      .1       0   114.8    .045       0     153      .1       0
Bank Sta=114.8,153
XS Rating Curve= 0 ,0
Exp/Cntr=0.3,0.1

Type RM Length L Ch R = 1 ,22247.3 ,403.9,392.6,380.8
XS GIS Cut Line= 2
     1763165.427       563612.86     1762872.024       563447.93
#Sta/Elev= 30
       0  670.77     9.6  666.18    19.2  661.35    28.8  656.27    48.1  646.21
    57.7  642.04    67.3  639.19    76.9  637.39    86.6   635.9    96.2  634.56
   105.8  633.43   115.4  632.47     125  631.71   144.2  630.77   163.5  629.01
   173.1  627.98   182.7  627.25   192.3  627.34     202   628.8   211.6  631.68
   221.2  635.06   230.8  638.73   240.4  643.87     250  650.57   278.9  671.87
   298.1  686.26   307.7   692.7   317.4  697.54     327  701.11   336.6  704.34
#Mann= 3 , 0 , 0
       0      .1       0   173.1    .045       0     202      .1       0
Bank Sta=173.1,202
XS Rating Curve= 0 ,0
Exp/Cntr=0.3,0.1