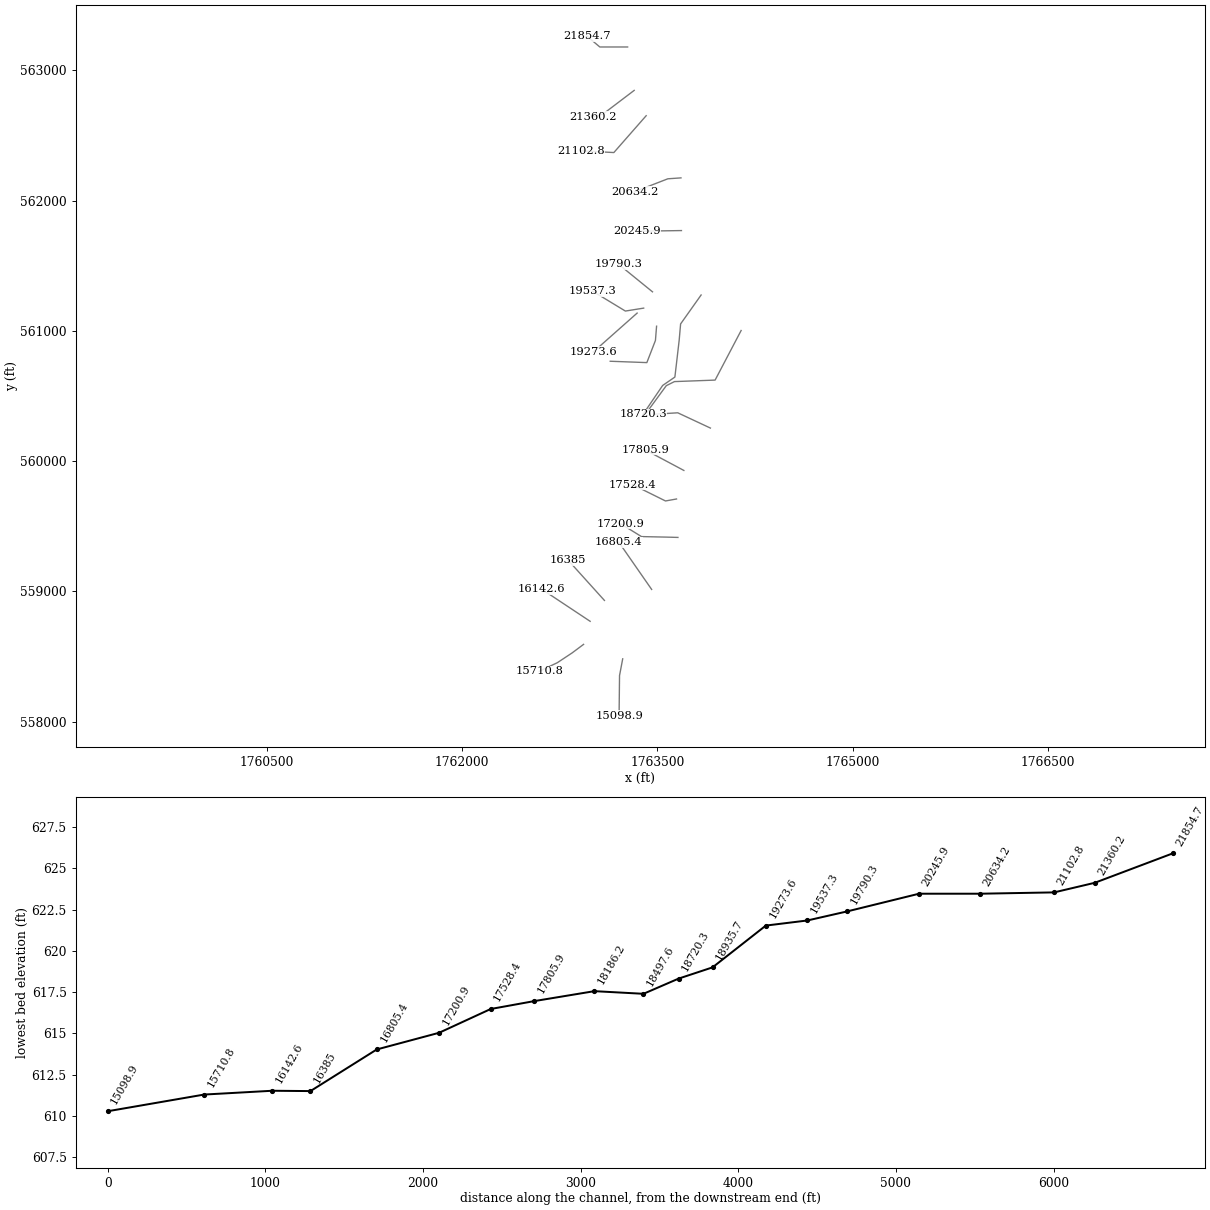
HEC-RAS study FROGCK.prj: FROGCK

--- FROGCK.g01 (geometry) --- (continued)

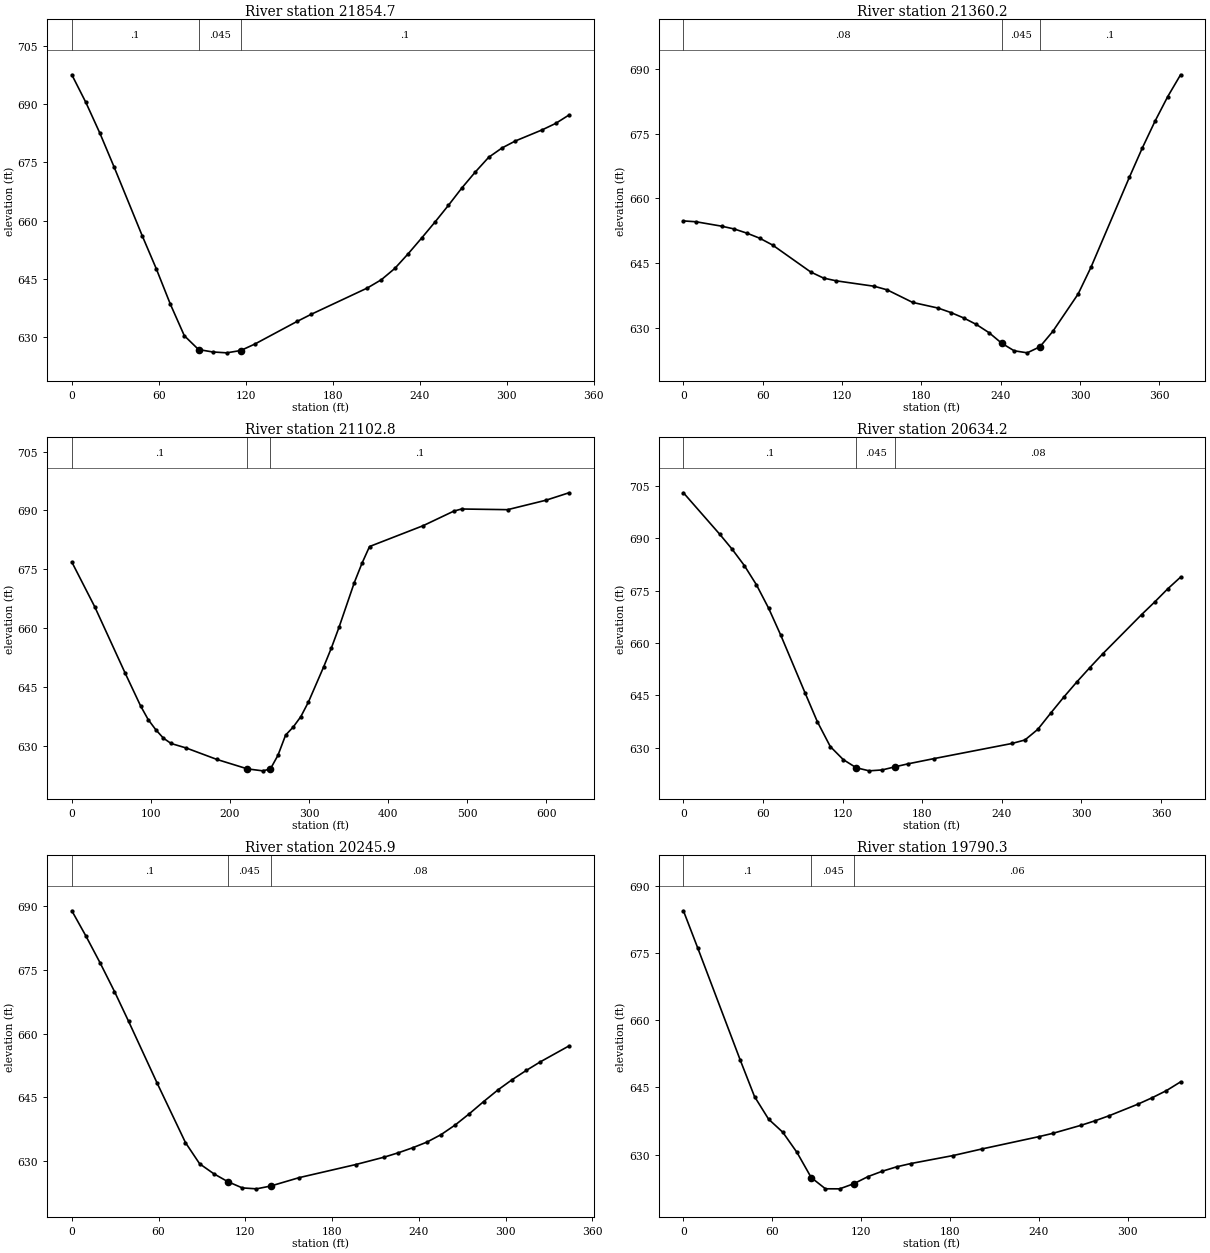
Type RM Length L Ch R = 1 ,21854.7 ,479.1,494.5,509.8
XS GIS Cut Line= 3
     1763271.329      563180.569     1763057.788      563180.569
     1762958.829      563263.902
#Sta/Elev= 30
       0  697.62     9.7  690.47    19.4  682.51    29.1  673.88    48.5  656.14
    58.2  647.63      68  638.41    77.6  630.31    87.4  626.75    97.1  626.13
   106.8   625.9   116.5   626.5   126.2  628.16   155.3  633.99     165  635.82
   203.8  642.62   213.5  644.76   222.8  647.68     232  651.46   241.3  655.52
   250.5  659.64   259.8  663.97     269  668.42   278.2   672.5   287.5  676.33
   296.7  678.74     306  680.56   324.4  683.41   333.7  685.07   342.9  687.24
#Mann= 3 , 0 , 0
       0      .1       0    87.4    .045       0   116.5      .1       0
Bank Sta=87.4,116.5
XS Rating Curve= 0 ,0
Exp/Cntr=0.3,0.1

Type RM Length L Ch R = 1 ,21360.2 ,253.2,257.5,261.2
XS GIS Cut Line= 3
     1763321.677      562847.235     1763083.829       562666.68
     1763009.177      562645.847
#Sta/Elev= 30
       0  654.75     9.6  654.55    28.9  653.53    38.5  652.87    48.2  651.89
    57.8  650.72    67.4  649.16    96.3  642.89     106  641.48   115.6  640.84
   144.5  639.57   154.1  638.75   173.4  635.83   192.7  634.51   202.3  633.48
   211.9  632.24   221.6  630.71   231.2   628.8   240.8  626.35   250.2   624.6
   260.1  624.12   269.7  625.53   279.4  629.08   298.6  637.78   308.3  643.97
   337.4   664.9   347.1  671.64   356.8  677.92   366.4  683.62   376.1  688.68
#Mann= 3 , 0 , 0
       0     .08       0   240.8    .045       0   269.7      .1       0
Bank Sta=240.8,269.7
XS Rating Curve= 0 ,0
Exp/Cntr=0.3,0.1

Type RM Length L Ch R = 1 ,21102.8 ,479.7,468.5,457.4
XS GIS Cut Line= 3
      1763413.69      562652.791     1763165.427      562369.805
      1762913.69      562383.694
#Sta/Elev= 30
       0  676.82      29  665.39    67.6   648.4    86.9  640.13    96.5  636.63
   106.2  634.02   115.8  631.88   125.5  630.52   144.8  629.36   183.4  626.45
     222  624.04   241.3  623.54     251     624   260.6  627.49   270.3  632.66
   279.9  634.71   289.6  637.39   299.2  641.12   318.5  650.11   328.2  654.91
   337.8  660.15   357.2   671.6   366.8  676.47   376.4  680.78   444.3  686.11
   483.1  689.83   492.8  690.36     551  690.19   599.5   692.6   628.6   694.5
#Mann= 3 , 0 , 0
       0      .1       0     222    .045       0     251      .1       0
Bank Sta=222,251
XS Rating Curve= 0 ,0
Exp/Cntr=0.3,0.1

Type RM Length L Ch R = 1 ,20634.2 ,396.3,388.3,380.3
XS GIS Cut Line= 3
     1763681.052       562175.36     1763580.357      562168.416
     1763325.149      562069.458
#Sta/Elev= 29
       0  702.93    27.5  691.02    36.7  686.81    45.9  682.14      55  676.65
    64.2  669.95    73.4   662.2    91.8  645.63   100.9  637.54   110.7   630.4
   120.5  626.66   130.3  624.34     140  623.46   149.8  623.72   159.6  624.62
   169.4  625.47   188.9  626.96   247.6  631.28   257.4  632.28   267.1  635.32
   276.9  639.99   286.7  644.54   296.4  648.82   306.2  652.92     316  656.89
   345.3  668.11   355.1  671.68   364.9  675.43   374.7  678.82
#Mann= 3 , 0 , 0
       0      .1       0   130.3    .045       0   159.6     .08       0
Bank Sta=130.3,159.6
XS Rating Curve= 0 ,0
Exp/Cntr=0.3,0.1

Type RM Length L Ch R = 1 ,20245.9 ,471.3,455.5,439.7
XS GIS Cut Line= 2
     1763684.524      561770.847     1763340.774      561765.638
#Sta/Elev= 28
       0  688.99     9.8     683    19.6  676.68    29.5  669.96    39.3   662.9
    58.9  648.44    78.6  634.35    88.4  629.36    98.2  627.01     108  625.13
   117.9  623.68   127.7  623.46   137.5  624.12   157.2   626.1   196.4  629.19
   216.1  630.94   225.9  631.97   235.7  633.14   245.6  634.48   255.4  636.25
   265.2  638.53     275  641.19   284.8  644.03   294.7  646.78   304.5  649.19
   314.3  651.37   324.1  653.41   343.8  657.14
#Mann= 3 , 0 , 0
       0      .1       0     108    .045       0   137.5     .08       0
Bank Sta=108,137.5
XS Rating Curve= 0 ,0
Exp/Cntr=0.3,0.1

Type RM Length L Ch R = 1 ,19790.3 ,249.9,253,256.1
XS GIS Cut Line= 2
     1763462.302       561300.36     1763201.885      561512.166
#Sta/Elev= 26
       0  684.39     9.6  676.15    38.4  651.07      48  642.97    57.5  637.93
    67.1  635.01    76.7   630.5    86.3   624.9    95.9   622.4   105.5  622.39
   115.1  623.54   124.7  625.13   134.3  626.32   143.9  627.29   153.4  628.02
   182.2  629.82   201.4  631.27   239.8  634.01   249.4  634.76   268.5  636.56
   278.1  637.58   287.7  638.72   306.9  641.27   316.5   642.7   326.1  644.28
   335.7  646.24
#Mann= 3 , 0 , 0
       0      .1       0    86.3    .045       0   115.1     .06       0
Bank Sta=86.3,115.1
XS Rating Curve= 0 ,0
Exp/Cntr=0.3,0.1

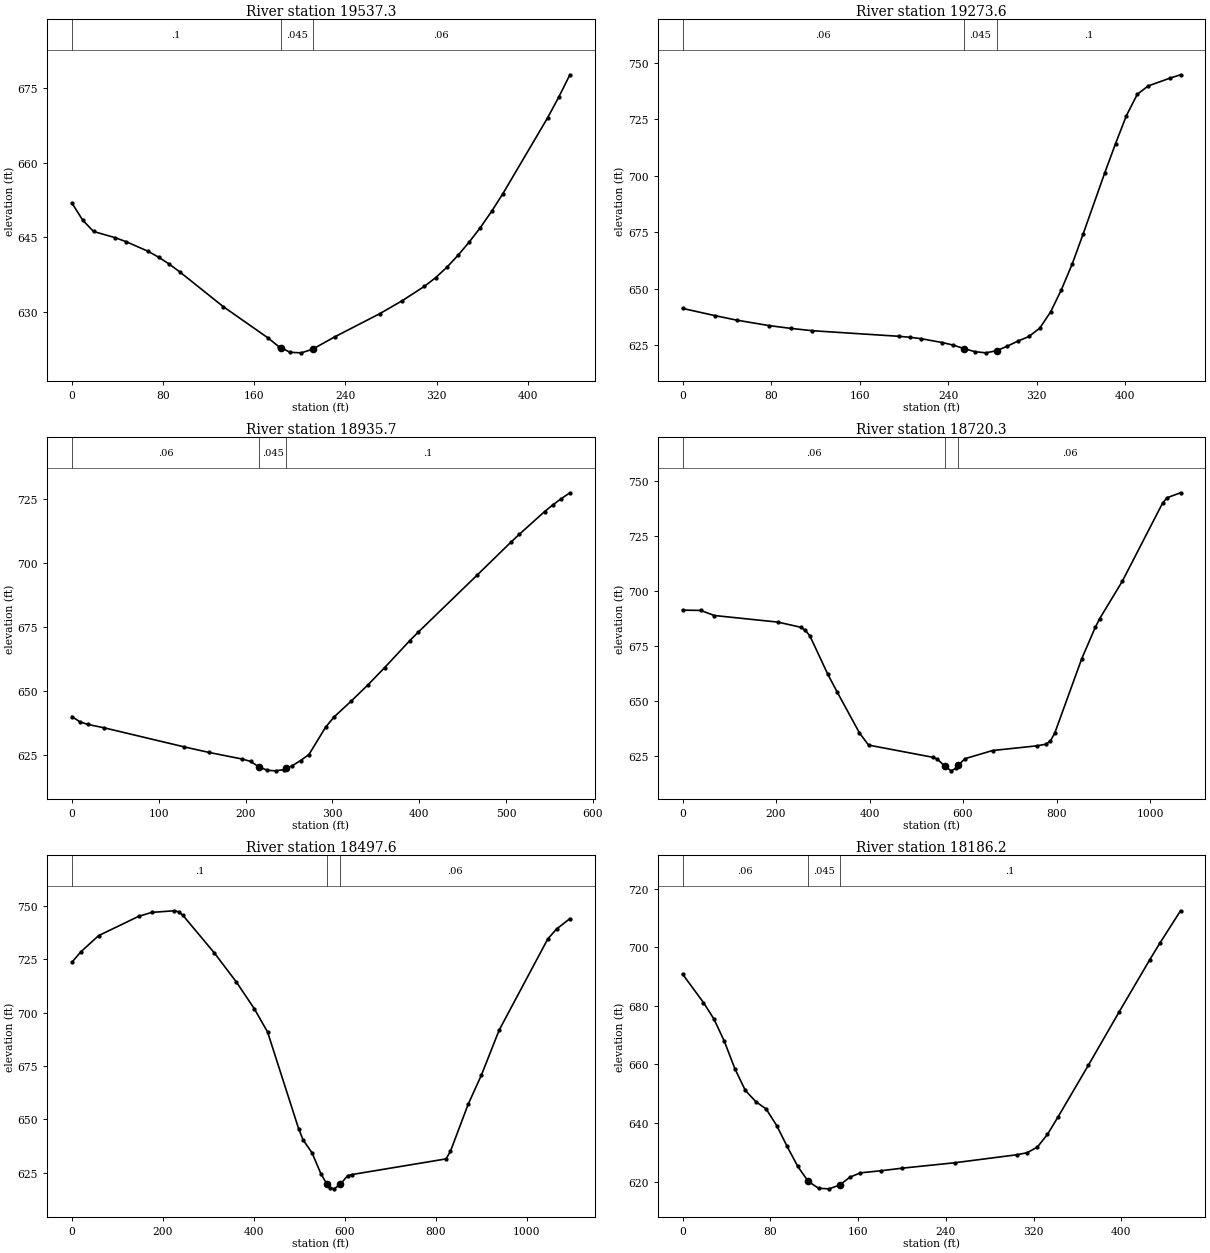
Type RM Length L Ch R = 1 ,19537.3 ,234.6,263.7,292.6
XS GIS Cut Line= 3
     1763394.593       561175.36     1763253.968      561152.791
     1763002.232      561305.569
#Sta/Elev= 30
       0   651.9     9.5  648.45      19  646.18      38  644.93    47.5  644.14
    66.5  642.24      76  641.04    85.4  639.64      95  638.01   132.9  631.09
   171.9  624.86   181.7  623.06   183.1   622.9   191.5  621.94   201.3  621.84
   211.1  622.56   230.8  625.07     270  629.68   289.7  632.28   309.3  635.18
   319.1  636.91   328.9  638.98   338.7  641.38   348.6  644.06   358.4  646.97
   368.2   650.2     378  653.71   417.3  668.95   427.1  673.11   436.9   677.6
#Mann= 3 , 0 , 0
       0      .1       0   183.1    .045       0   211.1     .06       0
Bank Sta=183.1,211.1
XS Rating Curve= 0 ,0
Exp/Cntr=0.3,0.1

Type RM Length L Ch R = 1 ,19273.6 ,327,338,348.6
XS GIS Cut Line= 2
     1763344.246      561137.166      1763007.44      560838.555
#Sta/Elev= 30
       0  641.22    29.4     638    48.9  636.02    78.3  633.59    97.8  632.36
   117.4  631.33   195.7  628.85   205.5  628.42   215.3  627.82   234.8  626.09
   244.6  624.96   254.4  623.41   264.2  622.06     274  621.53   283.8  622.45
   293.6   624.5   303.3  626.77   313.1  628.77   322.9  632.48   332.7  639.67
   342.5  649.56   352.3  660.99     362  674.05   381.6  701.21   391.4  714.22
   401.2  726.59     411  736.03   420.8  739.73   440.3  743.15   450.1  744.69
#Mann= 3 , 0 , 0
       0     .06       0   254.4    .045       0   283.8      .1       0
Bank Sta=254.4,283.8
XS Rating Curve= 0 ,0
Exp/Cntr=0.3,0.1

Type RM Length L Ch R = 1 ,18935.7 ,209.6,215.4,221.2
XS GIS Cut Line= 4
     1763493.552      561036.472     1763484.871      560927.097
     1763418.899      560756.958     1763137.649      560767.374
#Sta/Elev= 30
       0  640.19     9.1  638.16    18.3  637.11    36.6  635.84   128.9  628.39
   157.7   626.2   196.2   623.6   205.8  622.68   215.4  620.54     225  619.23
   234.6     619   244.2  619.46  247.16  619.98   253.8  620.98   263.4  623.02
     273  625.35   292.2     636   301.9  640.01   321.3  646.08   340.7  652.46
   360.1  659.24   389.2  669.83     399  673.16   466.9  695.44   505.7  708.27
   515.4  711.34   544.5  720.22   554.2  722.86   563.9   725.3   573.6  727.54
#Mann= 3 , 0 , 0
       0     .06       0   215.4    .045       0  247.16      .1       0
Bank Sta=215.4,247.16
XS Rating Curve= 0 ,0
Exp/Cntr=0.3,0.1

Type RM Length L Ch R = 1 ,18720.3 ,255,222.7,190
XS GIS Cut Line= 6
     1763835.565      561276.055     1763678.085       561053.94
     1763667.163      560928.833     1763634.177      560645.847
     1763540.427       560581.61     1763389.385      560359.388
#Sta/Elev= 30
       0  691.28    38.9  691.15    68.1  688.84   204.2  685.84   252.8  683.51
   262.6  682.12   272.3  679.63   310.9   662.1   330.2  654.33   378.5  635.51
   397.9  630.01   535.4  624.47   545.2  623.63  560.73  620.47   574.7  618.32
   584.5  619.44  590.21     621   604.2  623.84   663.1  627.54   758.5  629.69
   777.5  630.43   786.9  631.88   796.4  635.61     854  669.31   882.8  683.47
   892.4  687.48   940.4  704.32  1026.7  739.84  1036.3  742.31  1065.1  744.56
#Mann= 3 , 0 , 0
       0     .06       0  560.73    .045       0  590.21     .06       0
Bank Sta=560.73,590.21
XS Rating Curve= 0 ,0
Exp/Cntr=0.3,0.1

Type RM Length L Ch R = 1 ,18497.6 ,322.4,311.4,300.5
XS GIS Cut Line= 5
     1764142.857      561003.485     1763943.033      560622.692
     1763630.704      560611.124     1763568.204      560579.874
     1763401.538      560352.444
#Sta/Elev= 30
       0  723.52    19.6   728.4    58.6  735.99   146.6  745.04   175.9  746.91
   224.8  747.65   234.6   747.2   244.3  745.44   312.8  727.98   361.6  714.25
   400.7  701.83     430   690.9   498.4   645.5   508.2  640.27   527.7  634.31
   547.2  624.48   560.3  619.66   566.8  617.92   576.5   617.4  590.05  619.57
   605.8  623.54   615.6   624.1   822.2  631.42   831.9  634.97   870.8  656.98
     900   670.7   938.9  691.72  1045.8  734.44  1065.2  739.12  1094.4  743.97
#Mann= 3 , 0 , 0
       0      .1       0   560.3    .045       0  590.05     .06       0
Bank Sta=560.3,590.05
XS Rating Curve= 0 ,0
Exp/Cntr=0.3,0.1

Type RM Length L Ch R = 1 ,18186.2 ,381.2,380.3,379.3
XS GIS Cut Line= 3
     1763906.818      560254.354     1763656.167      560371.541
     1763479.301       560360.69
#Sta/Elev= 30
       0  690.87    19.1  681.13    28.6  675.54    38.2  667.86    47.7  658.56
    57.2  651.18    66.8  647.32    76.3  644.78    85.9  639.11    95.4  632.01
     105  625.24   114.5  620.14     124  617.75   133.6  617.56   143.1  618.84
   152.7  621.56   162.2  623.02   181.3  623.75   200.4  624.62   248.1  626.46
   304.7  629.19     314  629.88   323.3  631.77   332.6  636.11     342  641.93
     370  659.79   397.9   677.9   425.9  695.77   435.2  701.48   453.9  712.45
#Mann= 3 , 0 , 0
       0     .06       0   114.5    .045       0   143.1      .1       0
Bank Sta=114.5,143.1
XS Rating Curve= 0 ,0
Exp/Cntr=0.3,0.1

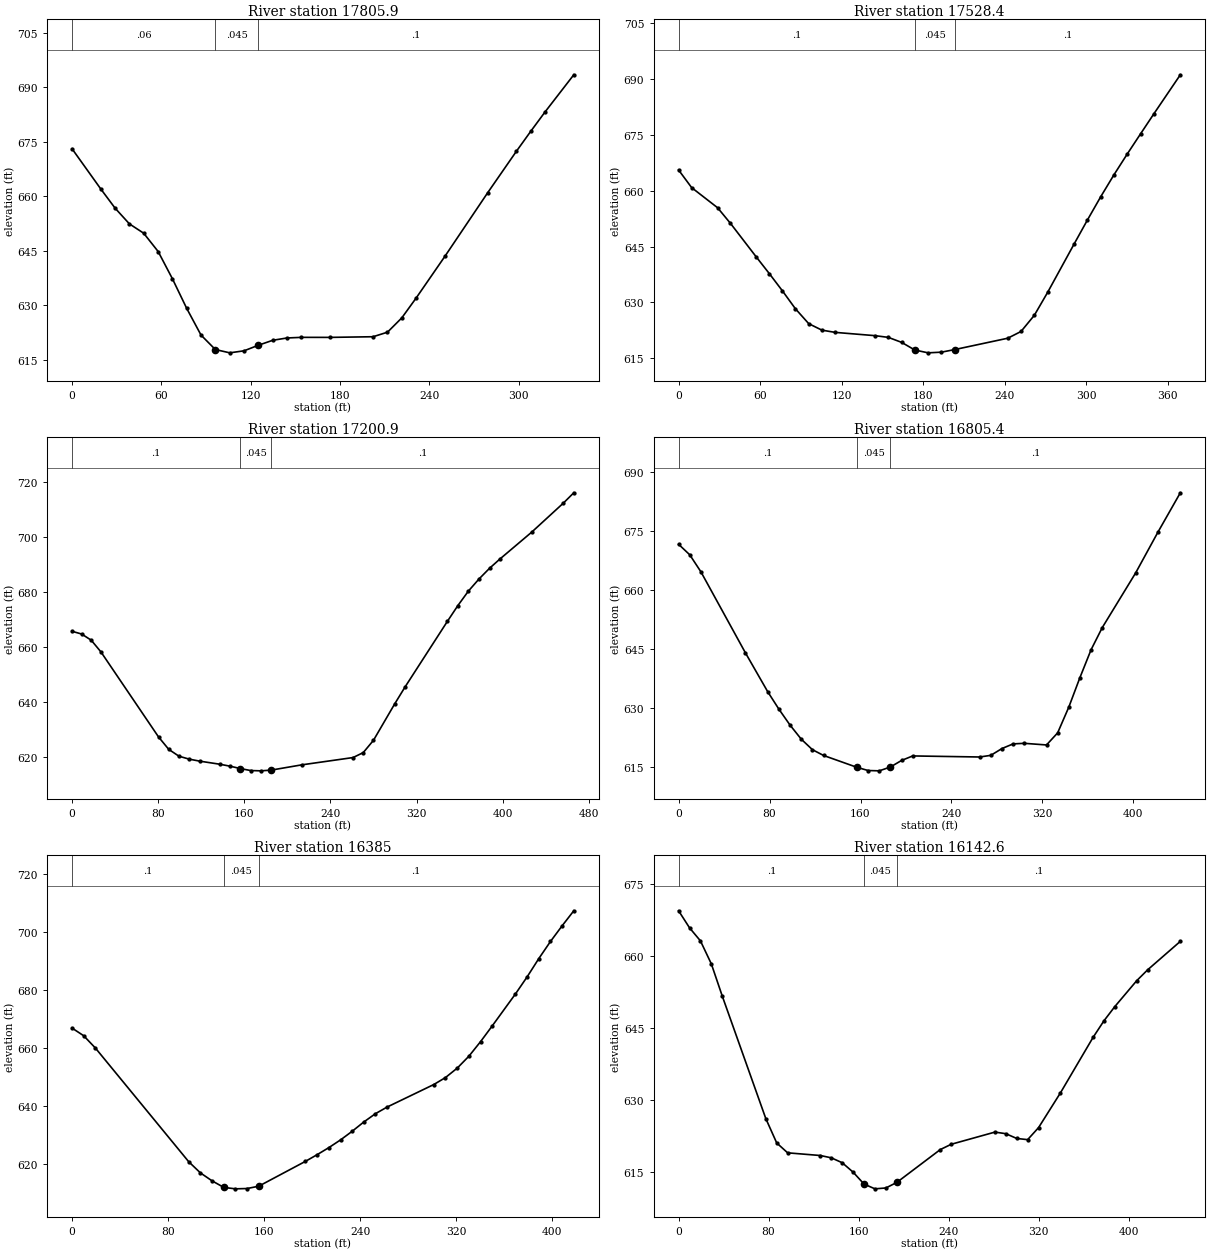
Type RM Length L Ch R = 1 ,17805.9 ,277.3,277.6,278.2
XS GIS Cut Line= 2
     1763703.097      559928.923     1763405.788      560087.343
#Sta/Elev= 27
       0  673.08    19.2  662.08    28.9  656.75    38.5  652.43    48.1  649.86
    57.8  644.83    67.4  637.32      77  629.17    86.6  621.84    96.2  617.87
   105.9  616.96   115.5  617.52   125.1  619.05   134.8  620.42   144.4  621.05
     154  621.22   173.2  621.21   202.1  621.39   211.8  622.64   221.4  626.57
     231  632.01   250.3  643.47   279.1  661.01   298.4  672.42     308  677.89
   317.6  683.22   336.9  693.44
#Mann= 3 , 0 , 0
       0     .06       0    96.2    .045       0   125.1      .1       0
Bank Sta=96.2,125.1
XS Rating Curve= 0 ,0
Exp/Cntr=0.3,0.1

Type RM Length L Ch R = 1 ,17528.4 ,318.6,327.4,337
XS GIS Cut Line= 3
     1763646.673      559709.739     1763562.038      559694.548
     1763308.131      559820.416
#Sta/Elev= 30
       0  665.55     9.6  660.82    28.7  655.42    38.2  651.22    57.3  642.16
    66.9  637.69    76.4  633.13      86  628.31    95.8  624.31   105.5  622.57
   115.3  621.97   144.6  621.09   154.4  620.63   164.2  619.29   173.9  617.24
   183.7  616.48   193.5  616.66   203.2  617.35   242.3   620.4   252.1  622.21
   261.9  626.55   271.7  632.71   291.2  645.69     301  652.13   310.8  658.38
   320.5  664.24   330.3  669.83   340.1  675.24   349.8  680.56   369.4   691.1
#Mann= 3 , 0 , 0
       0      .1       0   173.9    .045       0   203.2      .1       0
Bank Sta=173.9,203.2
XS Rating Curve= 0 ,0
Exp/Cntr=0.3,0.1

Type RM Length L Ch R = 1 ,17200.9 ,415.6,395.5,373.9
XS GIS Cut Line= 4
     1763657.524        559414.6     1763577.228       559416.77
     1763377.576      559421.111     1763219.156      559518.767
#Sta/Elev= 30
       0  665.69     8.9   664.7    17.8  662.46    26.8  658.22    80.3  627.36
    89.8  622.84    99.3  620.35   108.8  619.29   118.4  618.57   137.4  617.43
   146.9  616.72   156.4  615.86   165.9  615.15   175.4  615.04   184.9   615.3
   213.5  617.22     261  619.86   270.5  621.66     280  626.12   299.6  639.26
   309.4  645.52   348.6  669.26   358.4  675.02   368.2  680.29     378  684.66
   387.8  688.55   397.6  691.97     427  701.68   456.3  712.18   466.1  715.97
#Mann= 3 , 0 , 0
       0      .1       0   156.4    .045       0   184.9      .1       0
Bank Sta=156.4,184.9
XS Rating Curve= 0 ,0
Exp/Cntr=0.3,0.1

Type RM Length L Ch R = 1 ,16805.4 ,416.3,420.5,424.2
XS GIS Cut Line= 2
     1763455.701      559015.295     1763203.965      559377.708
#Sta/Elev= 30
       0  671.64     9.8  668.97    19.6  664.65    58.8  644.02    78.4  634.14
    88.2  629.72    98.1  625.63   107.9  622.08   117.7  619.41   127.5  617.94
   156.9  614.92   166.7  614.11   176.5  614.03   186.3  615.01   196.1  616.67
   205.9  617.82   264.8  617.55   274.6  617.97   284.4   619.7   294.2  620.88
     304  621.03   323.6  620.61   333.4  623.69   343.2  630.23     353  637.75
   362.8  644.83   372.6  650.44     402  664.36   421.6  674.73   441.3  684.74
#Mann= 3 , 0 , 0
       0      .1       0   156.9    .045       0   186.3      .1       0
Bank Sta=156.9,186.3
XS Rating Curve= 0 ,0
Exp/Cntr=0.3,0.1

Type RM Length L Ch R = 1 ,16385   ,237.1,242.4,247.9
XS GIS Cut Line= 2
     1763093.288      558930.659      1762813.34      559240.989
#Sta/Elev= 30
       0  666.82     9.7  664.18    19.4  659.97    97.2  620.82   106.9     617
   116.6  614.26   126.4     612   136.1  611.51   145.8  611.62   155.5  612.42
   194.4  620.97   204.1  623.26   213.8  625.67   223.6  628.34   233.3  631.31
     243  634.51   252.7  637.37   262.4  639.65   301.3   647.4     311  649.79
   320.8  653.04   330.5  657.13   340.2  662.13   349.9  667.53   369.3  678.56
   379.1  684.48   388.8  690.76   398.5  696.63   408.2  702.02   417.9  707.18
#Mann= 3 , 0 , 0
       0      .1       0   126.4    .045       0   155.5      .1       0
Bank Sta=126.4,155.5
XS Rating Curve= 0 ,0
Exp/Cntr=0.3,0.1

Type RM Length L Ch R = 1 ,16142.6 ,404.6,431.8,457.9
XS GIS Cut Line= 2
     1762983.478      558770.503     1762611.951      559017.031
#Sta/Elev= 30
       0  669.36     9.7  665.82    19.4   663.1    29.1  658.31    38.8  651.62
    77.5  626.14    87.2  621.07    96.9  619.02     126  618.46   135.7  617.98
   145.4  616.96   155.1     615   164.8  612.52   174.5  611.53   184.2  611.71
   193.9  612.86   232.6   619.7   242.3   620.8   281.1  623.33   290.8     623
   300.5  622.01   310.2  621.76   319.9  624.26   339.3  631.47   368.3  643.01
     378  646.47   387.7  649.44   407.1  654.81   416.8  657.07   445.9     663
#Mann= 3 , 0 , 0
       0      .1       0   164.8    .045       0   193.9      .1       0
Bank Sta=164.8,193.9
XS Rating Curve= 0 ,0
Exp/Cntr=0.3,0.1

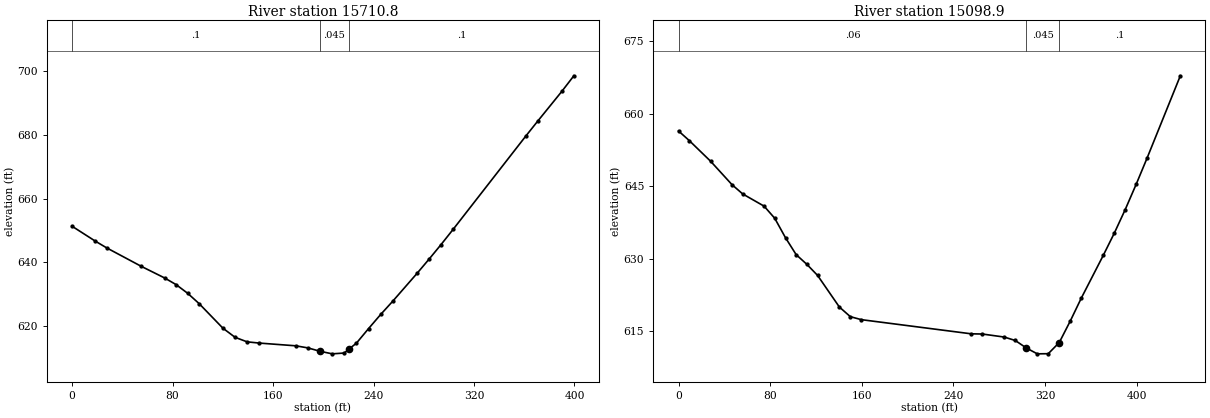
Type RM Length L Ch R = 1 ,15710.8 ,590,611.9,633.8
XS GIS Cut Line= 4
     1762933.131       558593.42      1762844.59      558527.447
     1762731.742      558452.795     1762592.853      558386.822
#Sta/Elev= 30
       0  651.36    18.4  646.71    27.6  644.56    55.2  638.75    73.6  635.14
    82.8  633.04      92  630.32   101.2  627.05   120.1  619.35   129.8  616.48
   139.4  615.06   149.1  614.68   178.1  613.82   187.7  613.17   197.4  612.11
   207.1   611.3   216.7  611.55  220.37  612.76   226.4  614.66   236.1  619.25
   245.7  623.66   255.3  627.82   274.6  636.54   284.2  641.02   293.8  645.62
   303.4  650.39     361  679.55   370.6   684.3   389.9  693.69   399.5   698.6
#Mann= 3 , 0 , 0
       0      .1       0   197.4    .045       0  220.37      .1       0
Bank Sta=197.4,220.37
XS Rating Curve= 0 ,0
Exp/Cntr=0.3,0.1

Type RM Length L Ch R = 1 ,15098.9 ,364.8,359.9,355.1
XS GIS Cut Line= 3
     1763233.478      558482.309     1763209.173      558353.836
     1763205.701      558046.545
#Sta/Elev= 30
       0  656.39     9.3  654.42      28  650.13    46.7  645.28      56  643.37
    74.7  640.84      84  638.33    93.4   634.3   102.7  630.81   112.1  628.79
   121.4  626.51   140.4  619.98     150  617.98   159.6  617.36   255.6  614.43
   265.2  614.39   284.4  613.76     294  613.05   303.6  611.51   313.2  610.29
   322.8  610.32   332.4  612.63     342  617.07   351.6   621.8   370.8  630.65
   380.4  635.23     390  640.14   399.6  645.39   409.2  650.86   438.1  667.81
#Mann= 3 , 0 , 0
       0     .06       0   303.6    .045       0   332.4      .1       0
Bank Sta=303.6,332.4
XS Rating Curve= 0 ,0
Exp/Cntr=0.3,0.1