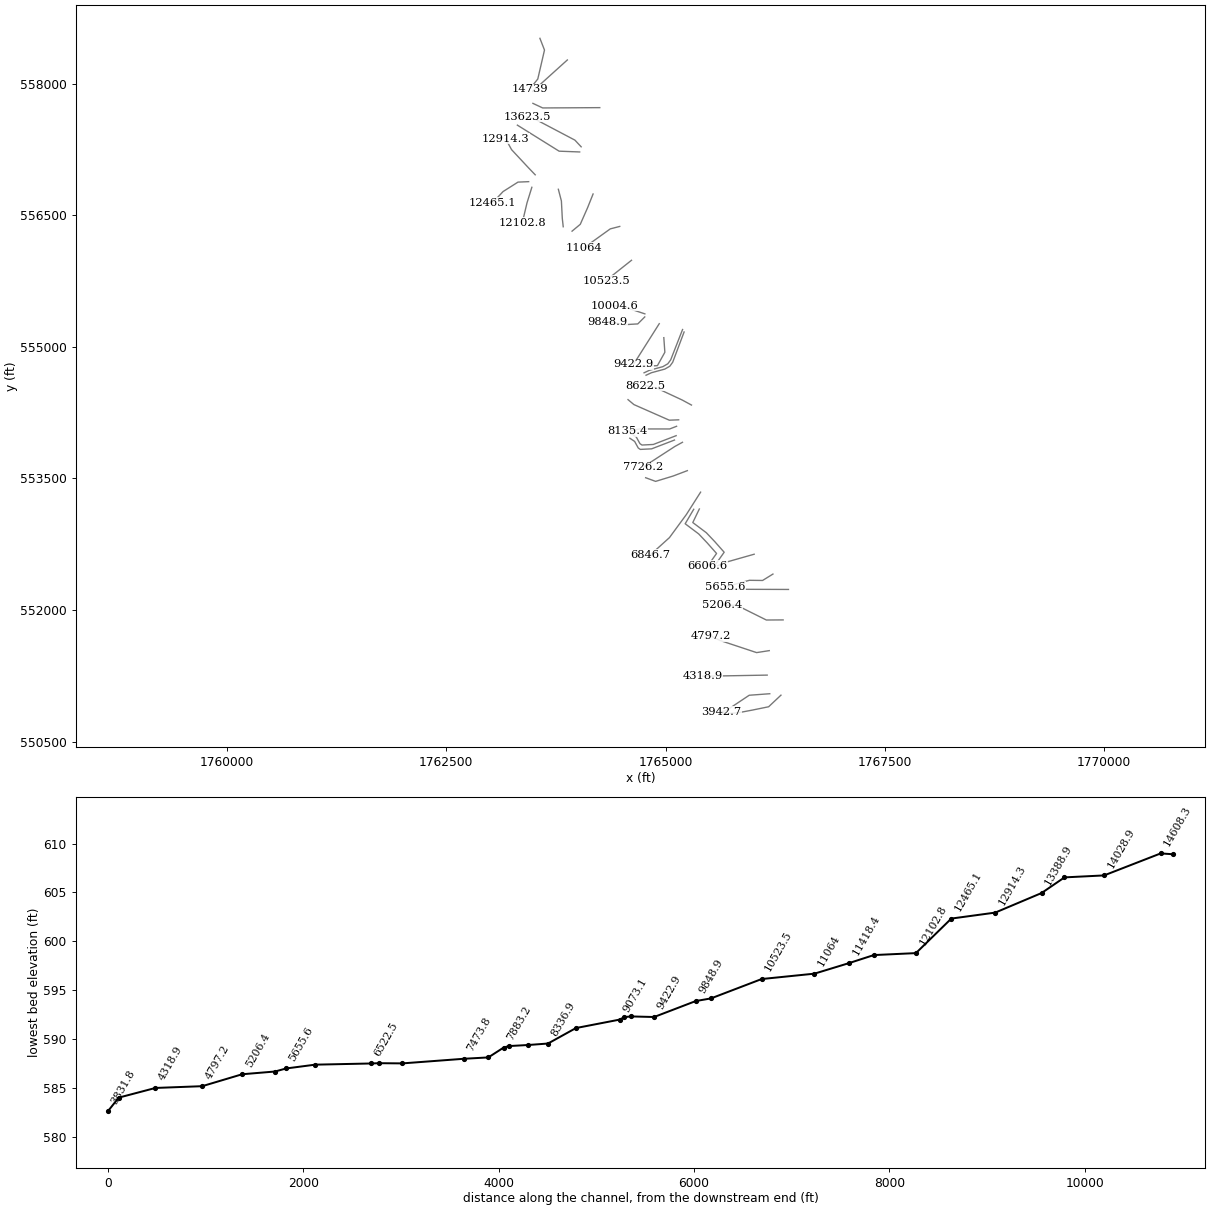
HEC-RAS study FROGCK.prj: FROGCK

--- FROGCK.g01 (geometry) --- (continued)

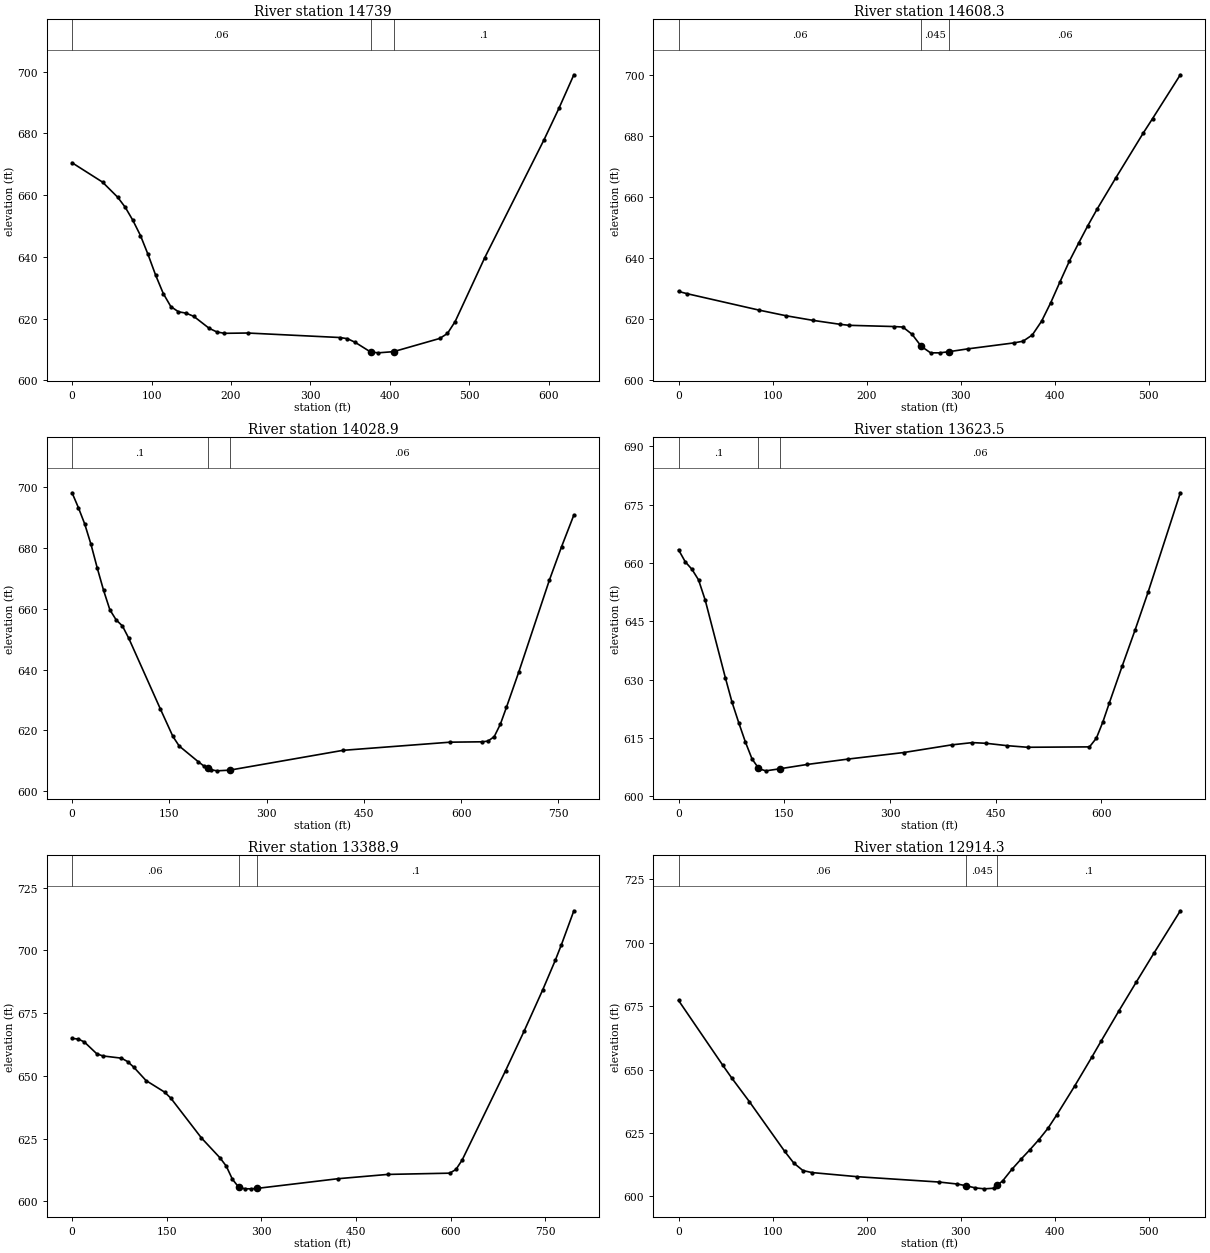
Type RM Length L Ch R = 1 ,14739   ,144.4,130.6,116.9
XS GIS Cut Line= 4
     1763568.548      558515.295     1763620.631      558381.614
     1763544.242      558051.753     1763450.492      557935.434
#Sta/Elev= 30
       0  670.46    38.3   664.2    57.4   659.3      67  656.01    76.5  651.82
    86.1  646.88    95.6  640.76   105.2  634.04   114.8   628.1   124.3  623.88
   133.9   622.2   143.5  621.75   153.1  620.73   172.5  616.85   182.2  615.67
   191.8  615.22   220.9  615.32     337  613.86   346.6  613.48   356.3   612.3
   375.6  609.19   385.3   608.9   404.7  609.29   462.7  613.56   472.4  615.17
   482.1  619.03   519.4  639.74   594.1  677.98   612.8  688.14   631.5  698.95
#Mann= 3 , 0 , 0
       0     .06       0   375.6    .045       0   404.7      .1       0
Bank Sta=375.6,404.7
XS Rating Curve= 0 ,0
Exp/Cntr=0.3,0.1

Type RM Length L Ch R = 1 ,14608.3 ,596.6,579.5,576.7
XS GIS Cut Line= 3
     1763881.048      558268.767     1763703.965      558109.045
     1763485.215      557911.128
#Sta/Elev= 29
       0  629.09     9.5  628.32    85.8  622.96   114.5  621.12   143.1  619.61
   171.7  618.33   181.2     618   228.9   617.6   238.5  617.43   248.3  615.06
   258.1   611.1     268  608.99   277.8  608.99   287.6  609.37   307.3  610.28
   356.5  612.24   366.3   612.8   376.1  614.83     386  619.35   395.8  625.45
   405.6  632.26   415.5  638.98   425.3  644.86   435.1  650.58     445  656.02
   464.6   666.1   494.1  680.94     504  685.67   533.5     700
#Mann= 3 , 0 , 0
       0     .06       0   258.1    .045       0   287.6     .06       0
Bank Sta=258.1,287.6
XS Rating Curve= 0 ,0
Exp/Cntr=0.3,0.1

Type RM Length L Ch R = 1 ,14028.9 ,417.8,405.3,398.2
XS GIS Cut Line= 3
      1764250.84      557725.364     1763599.798      557721.892
     1763488.687      557773.975
#Sta/Elev= 30
       0  698.12     9.7  693.26    19.4  687.93    29.2  681.15    38.9  673.34
    48.6  666.05    58.3  659.66      68  656.34    77.7  654.34    87.4  650.32
     136  627.15   155.5  618.04   165.2   614.9   194.3  609.79   204.1  608.19
  209.22   607.6   213.8  607.12   223.5  606.74   242.9  606.96   417.8  613.48
     583  616.16   631.6  616.28   641.3   616.5     651  617.98   660.5  622.09
   669.9  627.66   688.8  639.18     736  669.38   754.9  680.43   773.8  690.81
#Mann= 3 , 0 , 0
       0      .1       0  209.22    .045       0   242.9     .06       0
Bank Sta=209.22,242.9
XS Rating Curve= 0 ,0
Exp/Cntr=0.3,0.1

Type RM Length L Ch R = 1 ,13623.5 ,231.9,234.6,234.4
XS GIS Cut Line= 4
     1764038.643      557278.822     1763967.331       557354.96
     1763535.171      557582.641     1763422.324      557620.836
#Sta/Elev= 30
       0  663.39     9.5   660.3      19  658.37    28.4  655.64    37.9   650.4
    66.4   630.5    75.9  624.18    85.4  618.93    94.8  613.98   104.3  609.59
   113.3  607.28   114.1  607.07   123.9  606.54   143.4  607.06   182.5  608.18
   241.1  609.58   319.2  611.24   387.6  613.22   416.9   613.8   436.5  613.62
   465.8  613.02   495.1   612.6     583   612.7   592.8  614.94     602  619.11
   611.1  623.96   629.4  633.47   647.8   642.8   666.1  652.45   711.9  678.04
#Mann= 3 , 0 , 0
       0      .1       0   113.3    .045       0   143.4     .06       0
Bank Sta=113.3,143.4
XS Rating Curve= 0 ,0
Exp/Cntr=0.3,0.1

Type RM Length L Ch R = 1 ,13388.9 ,482.1,474.6,466.1
XS GIS Cut Line= 3
     1764021.673      557220.156      1763787.39      557228.984
     1763311.603      557525.711
#Sta/Elev= 30
       0  664.92     9.8  664.69    19.5   663.5    39.1  658.82    48.8  657.94
    78.2  657.06    87.9  655.71    97.7  653.48   117.2  648.13   146.5  643.54
   156.3  641.17   205.1  625.21   234.4  617.31   244.3  614.03   254.1  608.76
     264  605.63   273.8  604.97   283.6  604.94   293.5  605.13   421.4  608.98
   500.1  610.69   598.4  611.19   608.3  612.66   618.1   616.4     687  652.09
   716.5  667.92     746  684.39   765.7  696.05   775.5  702.33   795.2  715.84
#Mann= 3 , 0 , 0
       0     .06       0     264    .045       0   293.5      .1       0
Bank Sta=264,293.5
XS Rating Curve= 0 ,0
Exp/Cntr=0.3,0.1

Type RM Length L Ch R = 1 ,12914.3 ,416,449.3,482.3
XS GIS Cut Line= 4
     1763514.728      556959.739     1763436.603      557041.336
     1763245.631      557246.197     1763177.923      557369.461
#Sta/Elev= 30
       0  677.27    47.1  651.66    56.5  646.71    75.3  637.36     113  617.68
   122.6   613.1   132.3  610.16   141.9  609.36   190.2  607.73   277.2  605.62
   296.5  604.84   306.1  604.14   315.8   603.3   325.4  602.94   335.1  603.18
   338.8   604.3   344.8  606.11   354.4  610.57   364.1  614.58   373.7  618.36
   383.4   622.4     393  626.87   402.4  632.18   421.2  643.42   439.9   655.1
   449.3  661.12     468  672.91   486.8  684.48   505.5  695.84   533.7  712.63
#Mann= 3 , 0 , 0
       0     .06       0   306.1    .045       0   338.8      .1       0
Bank Sta=306.1,338.8
XS Rating Curve= 0 ,0
Exp/Cntr=0.3,0.1

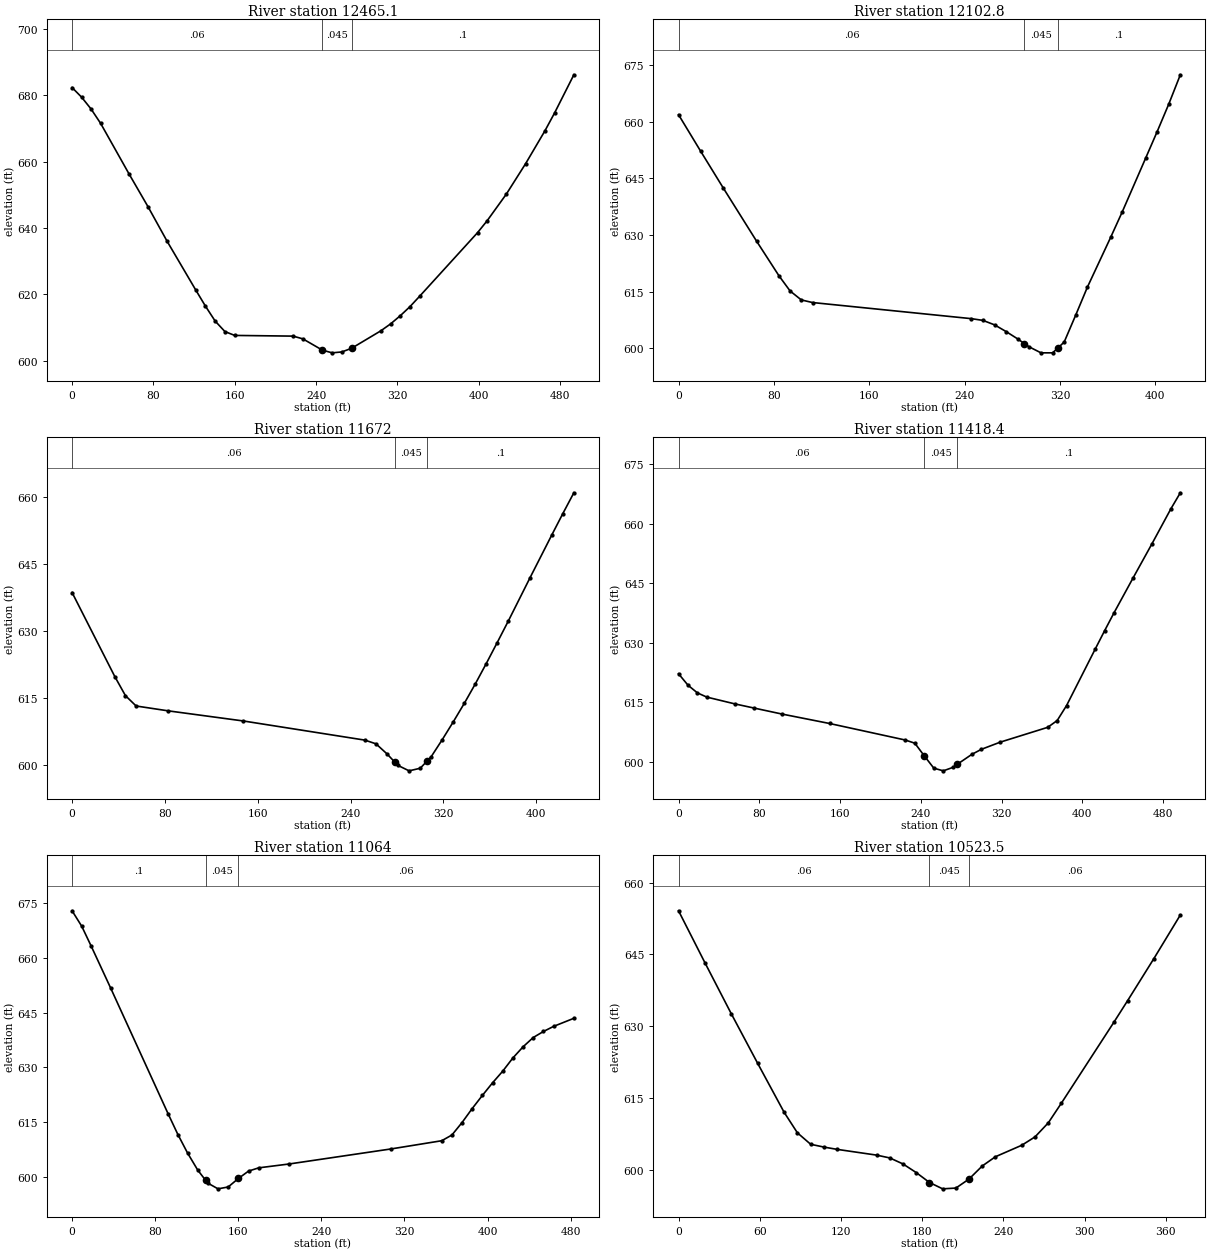
Type RM Length L Ch R = 1 ,12465.1 ,345.9,362.2,377.3
XS GIS Cut Line= 4
     1763440.076      556881.614     1763318.548      556876.406
     1763148.409      556768.767      1763032.09      556643.767
#Sta/Elev= 30
       0  682.31     9.4   679.4    18.7  675.84    28.1  671.51    56.1  656.24
    74.8  646.34    93.6  635.92   121.6  621.32   131.2  616.42   140.8   611.9
   150.4  608.74     160  607.58   217.5  607.37   227.1  606.54   246.3  603.14
   255.9  602.33   265.4   602.6     275   603.7   303.8  608.97   313.4  611.06
     323  613.54   332.4  616.24   341.9  619.37   398.9  638.55   408.3  642.12
   427.3   650.2   446.3   659.4   465.3   669.3   474.8  674.69   493.7  686.16
#Mann= 3 , 0 , 0
       0     .06       0   246.3    .045       0     275      .1       0
Bank Sta=246.3,275
XS Rating Curve= 0 ,0
Exp/Cntr=0.3,0.1

Type RM Length L Ch R = 1 ,12102.8 ,424.4,430.9,437.3
XS GIS Cut Line= 3
     1763476.534      556817.378     1763420.978      556638.559
     1763367.159      556411.128
#Sta/Elev= 27
       0  661.85    18.7  652.11    37.4  642.51    65.5  628.36    84.3  619.18
    93.6  615.18     103  612.81   112.4  612.12   245.7  607.85   255.4  607.39
   265.2   606.2   274.9  604.42   284.6  602.48  290.08  601.25   294.4  600.35
   304.1   598.8   313.8   598.8  318.42   600.1   323.6  601.69   333.3  608.84
   343.1  616.24   362.5  629.34   372.3  636.14   391.8  650.27   401.5  657.32
   411.2  664.58     421  672.42
#Mann= 3 , 0 , 0
       0     .06       0  290.08    .045       0  318.42      .1       0
Bank Sta=290.08,318.42
XS Rating Curve= 0 ,0
Exp/Cntr=0.3,0.1

Type RM Length L Ch R = 1 ,11672   ,264.2,253.6,243
XS GIS Cut Line= 4
     1763778.617      556794.809      1763813.34      556661.128
     1763823.756      556461.475     1763834.173      556367.725
#Sta/Elev= 26
       0  638.62    36.8  619.77      46  615.47    55.2  613.15    82.9  612.06
   147.6  609.79   252.4  605.49   261.9  604.66   271.4   602.4  278.38  600.48
   280.9  599.81   290.4   598.6     300  599.18  305.72  600.74   309.5  601.79
     319   605.6   328.5   609.6     338  613.75   347.5  618.12   356.9  622.67
   366.3  627.36   375.8  632.16   394.6  641.92   413.5  651.59   422.9  656.33
   432.4     661
#Mann= 3 , 0 , 0
       0     .06       0  278.38    .045       0  305.72      .1       0
Bank Sta=278.38,305.72
XS Rating Curve= 0 ,0
Exp/Cntr=0.3,0.1

Type RM Length L Ch R = 1 ,11418.4 ,365.8,354.4,343.5
XS GIS Cut Line= 4
     1764174.451      556740.989     1764111.951      556584.739
     1764028.617      556395.503     1763934.867      556317.378
#Sta/Elev= 28
       0  622.24     9.4  619.35    18.7  617.42      28  616.36    56.1  614.63
    74.8   613.6   102.8  612.07   149.6  609.71   224.7  605.54   234.1  604.74
   243.5  601.54   252.9  598.45   262.3  597.78   271.7  598.64  275.91  599.39
   290.5  601.92   299.9  603.19   318.7  605.01   365.7  608.74   375.1  610.45
   384.4  614.23   412.6  628.37     422  633.04   431.4  637.59   450.2  646.34
   468.9  654.94   487.7  663.78   497.1  667.84
#Mann= 3 , 0 , 0
       0     .06       0   243.5    .045       0  275.91      .1       0
Bank Sta=243.5,275.91
XS Rating Curve= 0 ,0
Exp/Cntr=0.3,0.1

Type RM Length L Ch R = 1 ,11064   ,539.1,540.5,539.7
XS GIS Cut Line= 3
      1764478.27      556371.197     1764370.631       556343.42
     1764068.548      556126.406
#Sta/Elev= 30
       0  672.99     9.3  668.75    18.5  663.24    37.1  651.82    92.6  617.21
   101.9  611.59   111.2  606.52     121  601.84   128.6  599.04   130.7  598.27
   140.5   596.7   150.3  597.21   160.1  599.54   169.9  601.57   179.7  602.46
     209  603.52   306.9  607.64   355.9   609.9   365.7  611.47   375.4  614.87
   385.2  618.72     395  622.32   404.8  625.78   414.6  628.98   424.4  632.61
   434.2  635.67     444  638.22   453.8  639.87   463.5  641.26   483.1  643.49
#Mann= 3 , 0 , 0
       0      .1       0   128.6    .045       0   160.1     .06       0
Bank Sta=128.6,160.1
XS Rating Curve= 0 ,0
Exp/Cntr=0.3,0.1

Type RM Length L Ch R = 1 ,10523.5 ,541.6,518.9,495.5
XS GIS Cut Line= 2
     1764612.385      555985.347      1764322.02      555754.878
#Sta/Elev= 27
       0  654.11    19.5  643.28      39  632.63    58.5  622.29      78  612.11
    87.8  607.83    97.6  605.44   107.3  604.86   117.1  604.38   146.3  603.18
   156.1  602.59   165.8  601.34   175.6  599.54   185.4  597.47   195.1  596.15
   204.9  596.31   214.6  598.19   224.4  600.92   234.1  602.84   253.6  605.24
   263.4  606.99   273.2  609.92   282.9  614.04   321.9     631   331.7  635.35
   351.2  644.16   370.7  653.23
#Mann= 3 , 0 , 0
       0     .06       0   185.4    .045       0   214.6     .06       0
Bank Sta=185.4,214.6
XS Rating Curve= 0 ,0
Exp/Cntr=0.3,0.1

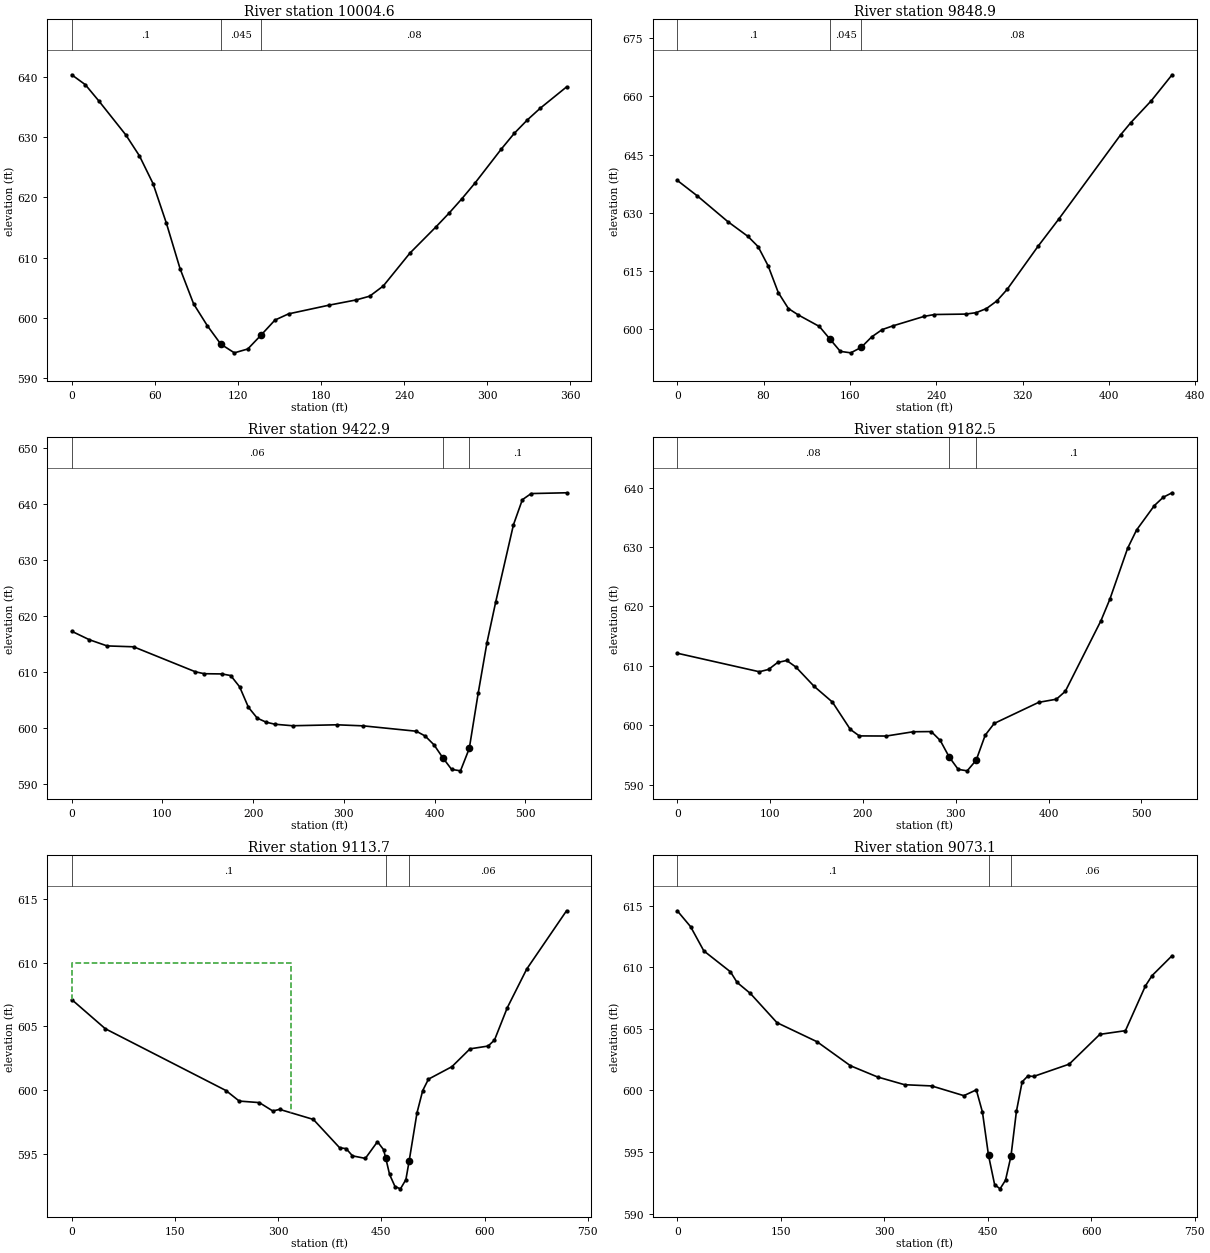
Type RM Length L Ch R = 1 ,10004.6 ,147.2,155.8,164.5
XS GIS Cut Line= 3
     1764764.728       555374.67     1764542.072      555448.888
     1764420.978      555467.118
#Sta/Elev= 30
       0  640.35     9.8  638.71    19.6     636    39.1  630.35    48.9  626.88
    58.7  622.28    68.4  615.66    78.2  608.16      88   602.3    97.8  598.71
   107.6  595.62   117.4  594.17   127.1  594.81   136.9  597.17   146.7  599.61
   156.5  600.64   185.8  602.09   205.4  602.96   215.1  603.58   224.9  605.27
   244.1  610.72     263   615.1   272.4  617.37   281.8   619.8   291.2  622.39
   310.1  628.01   319.5  630.63   328.9  632.85   338.3  634.81   357.2  638.33
#Mann= 3 , 0 , 0
       0      .1       0   107.6    .045       0   136.9     .08       0
Bank Sta=107.6,136.9
XS Rating Curve= 0 ,0
Exp/Cntr=0.3,0.1

Type RM Length L Ch R = 1 ,9848.9  ,403.6,426,447.6
XS GIS Cut Line= 4
     1764763.426      555339.513     1764683.999      555260.086
     1764529.051      555250.972     1764341.551       555287.43
#Sta/Elev= 30
       0  638.36    18.7  634.33    46.8  627.74    65.5  623.92    74.9  621.29
    84.2  616.34    93.6  609.45     103  605.32   112.3  603.65   131.7   600.7
   141.4  597.48   151.1  594.28   160.8   593.9   170.5  595.31   180.2  598.01
   189.9  599.89   199.6  600.83   228.7  603.29   238.4  603.78   267.5  603.89
   277.1  604.26   286.6  605.32   296.2  607.28   305.7  610.24   334.4  621.38
   353.5  628.35   410.8  650.06   420.4  653.26   439.4  658.91   458.6  665.58
#Mann= 3 , 0 , 0
       0      .1       0   141.4    .045       0   170.5     .08       0
Bank Sta=141.4,170.5
XS Rating Curve= 0 ,0
Exp/Cntr=0.3,0.1

Type RM Length L Ch R = 1 ,9422.9  ,238.9,240.4,241.5
XS GIS Cut Line= 2
     1764928.791       555262.69     1764637.124      554801.753
#Sta/Elev= 30
       0  617.22    19.5   615.7      39   614.6    68.2  614.44   136.4  609.97
   146.1  609.63   165.6  609.59   175.3   609.3   185.1  607.29   194.8  603.63
   204.6  601.68   214.3  600.97     224   600.6   243.5  600.33   292.2   600.5
   321.4  600.31   379.9  599.35   389.6   598.5   399.4  596.92   409.1  594.61
   418.8  592.53   428.6  592.27   438.3  596.28   448.1  606.14   457.8  615.19
   467.5   622.5     487  636.26   496.8  640.73   506.5  641.83   545.5  641.97
#Mann= 3 , 0 , 0
       0     .06       0   409.1    .045       0   438.3      .1       0
Bank Sta=409.1,438.3
XS Rating Curve= 0 ,0
Exp/Cntr=0.3,0.1

Type RM Length L Ch R = 1 ,9182.5  ,82.9,68.8,50.3
XS GIS Cut Line= 4
     1764980.874      555103.402     1764992.593      554936.736
     1764907.958      554784.392     1764716.551      554773.975
#Sta/Elev= 30
       0  612.13    88.4  609.01    98.3   609.4   108.1  610.57   117.9  610.91
   127.8   609.8   147.4  606.56   167.1  603.91   186.4  599.31   196.1  598.21
   225.2  598.19   254.2  598.91   273.6  598.94   283.3  597.44   292.9  594.66
   302.6  592.58   312.3  592.33     322  594.13   331.7  598.33   341.4  600.31
   389.3  603.86   408.4  604.39     418  605.72   456.4  617.61     466  621.23
   485.1  629.79   494.7  632.86   513.9  636.98   523.5  638.39     533  639.14
#Mann= 3 , 0 , 0
       0     .08       0   292.9    .045       0     322      .1       0
Bank Sta=292.9,322
XS Rating Curve= 0 ,0
Exp/Cntr=0.3,0.1

Type RM Length L Ch R = 1 ,9113.7  ,37.3,40.6,41
XS GIS Cut Line= 6
     1765194.459       555196.14     1765059.433      554850.798
     1765026.447      554805.659     1764969.156      554772.673
     1764816.812       554731.44     1764755.614      554702.795
#Sta/Elev= 30
       0  607.11    48.8  604.82   224.1  599.97   243.5  599.14   272.7  599.02
   292.3  598.36   302.1  598.49   351.2   597.7   389.5  595.47   398.8  595.41
   408.1  594.84   426.8  594.64   444.4  595.95   453.2  595.33  456.33  594.69
     462  593.38   469.9  592.43   477.8  592.25   485.7  592.97  490.35   594.4
   501.9  598.23   510.2  599.97   518.5  600.86   552.6  601.84   578.9  603.24
   605.2  603.46   614.5  603.93   633.1  606.47   661.3   609.5   719.2  614.08
#Mann= 3 , 0 , 0
       0      .1       0  456.33    .045       0  490.35     .06       0
#XS Ineff= 2 , 0
       0     318     610               0
Permanent Ineff=
       F       F
Bank Sta=456.33,490.35
XS Rating Curve= 0 ,0
Exp/Cntr=0.3,0.1

Type RM Length L Ch R = 1 ,9073.1  ,473.8,450.7,434.5
XS GIS Cut Line= 6
      1765211.82      555167.928     1765082.003       554823.02
     1765049.017      554777.881     1764991.725      554744.895
     1764839.381      554703.663     1764778.183      554675.017
#Sta/Elev= 30
       0   614.6    19.3  613.31    38.5  611.34    77.1  609.64    86.7  608.78
     106  607.88   144.5  605.51   202.6  603.96     251  602.01   290.2   601.1
   329.4  600.47   368.7  600.37   415.3  599.58   433.4  600.05   442.3  598.24
   451.1  594.72   459.9  592.36   467.8  592.01   475.7  592.71   483.6  594.66
   491.5   598.3   499.8   600.7   508.1  601.18   516.4  601.14     568  602.14
   612.4  604.56   649.5  604.86   678.5   608.5   688.2  609.34   717.1  610.95
#Mann= 3 , 0 , 0
       0      .1       0   451.1    .045       0   483.6     .06       0
Bank Sta=451.1,483.6
XS Rating Curve= 0 ,0
Exp/Cntr=0.3,0.1

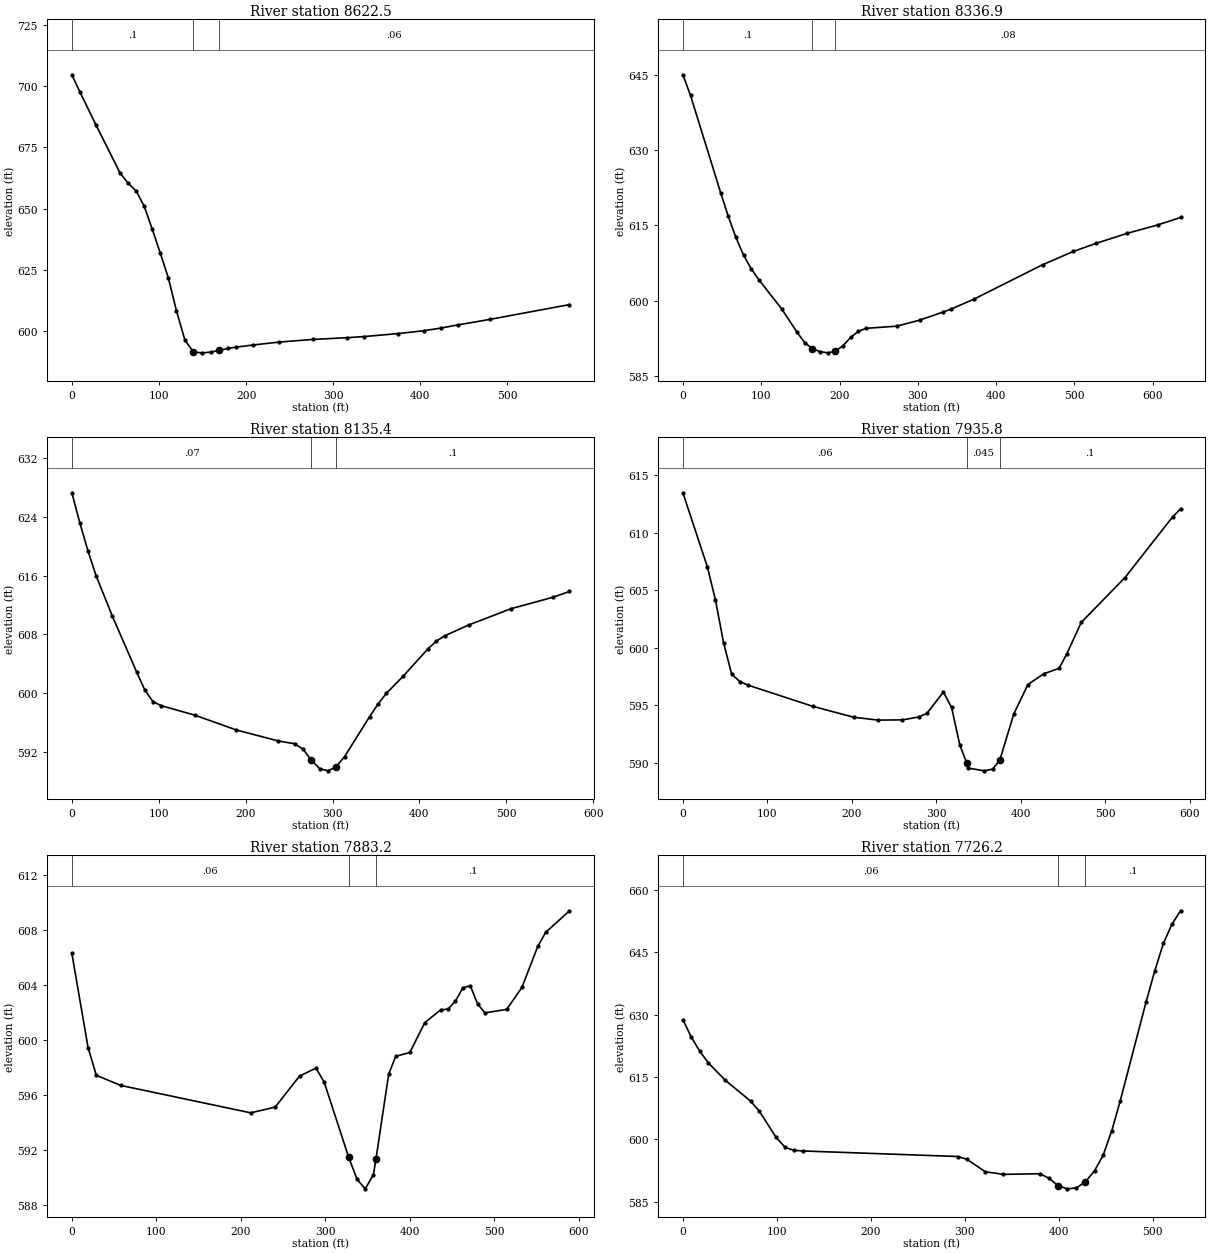
Type RM Length L Ch R = 1 ,8622.5  ,283.9,285.6,287.2
XS GIS Cut Line= 4
     1765295.978      554335.173      1765190.51      554392.465
     1764897.541      554529.184     1764772.541      554556.527
#Sta/Elev= 29
       0  704.69     9.2  697.71    27.7   684.2    55.4  664.55    64.6   660.4
    73.9  657.22    83.1  650.96    92.3  641.63   101.6  631.78   110.8   621.7
     120  608.42   129.8  596.34   139.6  591.49   149.4  591.14   159.2  591.41
     169  592.17   178.8  592.93   188.6  593.47   208.2  594.35   237.6  595.52
   276.8  596.61     316  597.33   335.6  597.79   374.8  599.02   404.1  600.17
   423.7  601.26   443.3  602.55   479.9   604.8   571.3  610.84
#Mann= 3 , 0 , 0
       0      .1       0   139.6    .045       0     169     .06       0
Bank Sta=139.6,169
XS Rating Curve= 0 ,0
Exp/Cntr=0.3,0.1

Type RM Length L Ch R = 1 ,8336.9  ,192.1,201.5,211.2
XS GIS Cut Line= 4
     1765149.928      554166.879     1765043.591      554162.539
     1764639.945       554340.49     1764572.671      554396.914
#Sta/Elev= 30
       0  645.07     9.7  640.95    48.4  621.43      58  616.79    67.7  612.59
    77.4  609.09    87.1  606.35    96.8  604.19     126  598.36   145.6  593.71
   155.4  591.62   165.2  590.39     175  589.81   184.8  589.56   194.6  589.87
   204.4  590.99   214.3  592.65   224.1  593.86   233.9  594.45   273.1  594.89
   302.5   596.1   331.9  597.69   341.7  598.25   371.1  600.24   459.3  607.15
   498.5   609.8     528  611.44   567.1  613.41   606.1  615.09   635.4  616.58
#Mann= 3 , 0 , 0
       0      .1       0   165.2    .045       0   194.6     .08       0
Bank Sta=165.2,194.6
XS Rating Curve= 0 ,0
Exp/Cntr=0.3,0.1

Type RM Length L Ch R = 1 ,8135.4  ,196.5,199.6,200.2
XS GIS Cut Line= 4
     1765126.057      554093.094     1765047.932      554062.712
      1764702.88      554062.712      1764561.82        554034.5
#Sta/Elev= 30
       0   627.3     9.3  623.14    18.6  619.36    27.9     616    46.6  610.49
    74.5  602.89    83.8  600.46    93.4  598.82     103  598.29   141.3     597
   189.3  594.98   237.2  593.49   256.4   593.1   265.9  592.38   275.5  590.88
   285.1  589.72   294.7  589.41   303.9  589.94   313.9  591.36   342.6  596.78
   352.2  598.48   361.8  599.95     381  602.27   409.7  606.02   419.3  607.06
   428.9   607.8   457.6  609.33   505.6  611.51   553.6  613.06   572.7  613.85
#Mann= 3 , 0 , 0
       0     .07       0   275.5    .045       0   303.9      .1       0
Bank Sta=275.5,303.9
XS Rating Curve= 0 ,0
Exp/Cntr=0.3,0.1

Type RM Length L Ch R = 1 ,7935.8  ,54.6,52.6,51.8
XS GIS Cut Line= 6
     1765121.499      553986.215     1764861.083      553885.954
     1764732.176      553879.444     1764708.739      553895.069
     1764667.072       553970.59     1764612.385      554007.048
#Sta/Elev= 30
       0  613.47    28.9  607.04    38.5  604.16    48.1  600.44    57.7   597.7
    67.4  597.06      77  596.75     154   594.9   202.1  593.96   230.9  593.71
   259.8  593.73     279  593.98   288.8   594.3   308.2  596.15   317.9  594.81
   327.6  591.56  335.87  589.97   337.4  589.54   356.8   589.3   366.5  589.45
   374.9  590.22   391.5  594.24   408.2   596.8     427  597.74   445.1  598.21
   453.9  599.42   471.4  602.21   523.1   606.1   579.5  611.38   588.8  612.07
#Mann= 3 , 0 , 0
       0     .06       0  335.87    .045       0   374.9      .1       0
Bank Sta=335.87,374.9
XS Rating Curve= 0 ,0
Exp/Cntr=0.3,0.1

Type RM Length L Ch R = 1 ,7883.2  ,145.5,157.1,168.4
XS GIS Cut Line= 6
     1765102.402      553936.302     1764841.985      553836.041
     1764713.079      553829.531     1764689.642      553845.156
     1764647.975      553920.677     1764593.288      553957.135
#Sta/Elev= 30
       0  606.31    19.2  599.44    28.9  597.43    57.7  596.69   211.7  594.69
   240.6  595.11   269.4  597.37   288.8  597.95   298.5  596.94   327.6  591.44
   337.4  589.85   347.1  589.15   356.8  590.18  359.79  591.31   374.9  597.52
   383.2  598.81   399.9  599.09   417.6  601.27   436.4   602.2   445.1  602.25
   453.9  602.84   462.6   603.8   471.4  603.96   480.1  602.63   488.7  601.98
   514.5  602.23   532.5  603.83   551.3  606.83   560.7  607.85   588.8  609.42
#Mann= 3 , 0 , 0
       0     .06       0   327.6    .045       0  359.79      .1       0
Bank Sta=327.6,359.79
XS Rating Curve= 0 ,0
Exp/Cntr=0.3,0.1

Type RM Length L Ch R = 1 ,7726.2  ,258.8,252.4,245.8
XS GIS Cut Line= 4
     1765193.331      553910.802     1765106.525      553863.059
     1764822.237      553678.598     1764748.452      553624.344
#Sta/Elev= 30
       0   628.8       9  624.57      18  621.21      27  618.44      45  614.26
      72  609.22    81.1  606.87    99.1  600.54   108.8  598.08   118.4   597.4
   128.1  597.24   292.7  595.91   302.4  595.21   321.8  592.24   341.1  591.62
   379.9  591.77   389.6  590.68   399.2   588.9   408.9  588.14   418.6  588.36
   428.3  589.82     438  592.49   447.1  596.17   456.3  602.08   465.4  609.35
   492.9  633.11   502.1  640.53   511.2  647.11   520.4  651.75   529.5  654.97
#Mann= 3 , 0 , 0
       0     .06       0   399.2    .045       0   428.3      .1       0
Bank Sta=399.2,428.3
XS Rating Curve= 0 ,0
Exp/Cntr=0.3,0.1

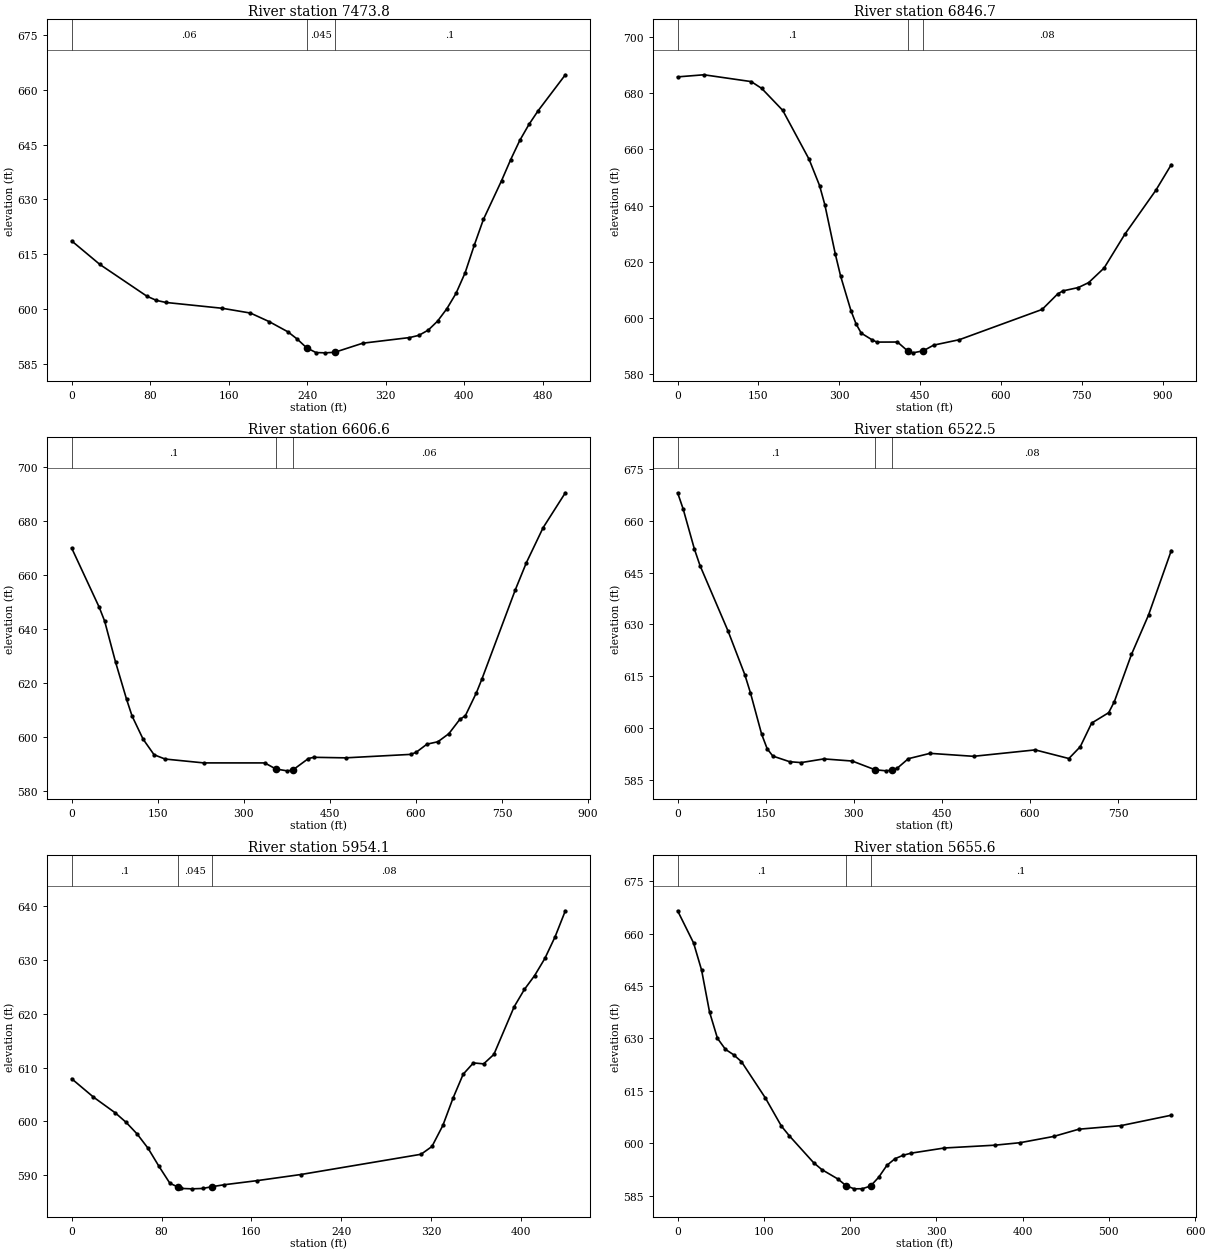
Type RM Length L Ch R = 1 ,7473.8  ,613.7,627.1,640.3
XS GIS Cut Line= 4
     1765248.995       553587.56     1765087.537      553526.362
     1764887.016      553465.164     1764773.735      553506.831
#Sta/Elev= 30
       0  618.65    28.8  612.19    76.7   603.5    86.3  602.37    95.9   601.8
   153.5   600.2   182.2  598.89   201.3  596.54   220.3  593.76   229.8  591.77
   239.4  589.38   248.9  588.08   258.4     588     268  588.15   296.6  590.64
   344.2  592.18   353.7  592.78   363.3  594.22   372.8  596.68   382.3  600.09
   391.6  604.28   400.9  609.93   410.2  617.47   419.5  624.52     438  635.14
   447.3   640.9   456.6  646.18   465.9  650.53   475.2  654.27     503  664.14
#Mann= 3 , 0 , 0
       0     .06       0   239.4    .045       0     268      .1       0
Bank Sta=239.4,268
XS Rating Curve= 0 ,0
Exp/Cntr=0.3,0.1

Type RM Length L Ch R = 1 ,6846.7  ,176.2,240.1,275.4
XS GIS Cut Line= 4
     1765400.044      553342.363     1765237.717      553087.155
     1765045.009      552824.134     1764831.467      552631.426
#Sta/Elev= 30
       0  685.81    48.8  686.56   136.6  684.13   156.1   681.7   195.1  673.88
   243.9   656.5   263.4  647.12   273.2  640.28   292.7  622.67   302.5  614.86
   321.6   602.6   331.2  597.82   340.8  594.54     360  592.27   369.6  591.36
     408  591.38   427.1  588.18   436.7  587.53   455.9  588.25   475.1  590.27
     523  592.22   676.5  602.99   705.2  608.48   714.8  609.58   743.6  610.78
   762.8  612.54   791.5  617.74   829.9  629.75   887.4  645.39   916.2  654.56
#Mann= 3 , 0 , 0
       0      .1       0   427.1    .045       0   455.9     .08       0
Bank Sta=427.1,455.9
XS Rating Curve= 0 ,0
Exp/Cntr=0.3,0.1

Type RM Length L Ch R = 1 ,6606.6  ,108.8,84.1,89
XS GIS Cut Line= 6
     1765321.485      553147.051     1765224.263       552982.12
     1765378.777      552865.801     1765474.263      552765.107
     1765581.902      552643.579     1765481.207      552501.218
#Sta/Elev= 30
       0  670.03    47.9  648.16    57.4  643.03    76.6  627.73    95.7  614.02
   105.3  607.83   124.4  599.31   143.6  593.51   162.7  591.92   230.1  590.49
   336.5  590.48   355.8  588.24   375.2  587.55   384.9  587.78   412.6  592.11
   421.9  592.56   477.4  592.36   590.5  593.64     600  594.36   619.1  597.42
   638.2  598.32   657.3   601.3   676.4   606.6     686  607.93   705.3  616.46
     715  621.58   773.2  654.61   792.5  664.66   821.6  677.58   860.3  690.49
#Mann= 3 , 0 , 0
       0      .1       0   355.8    .045       0   384.9     .06       0
Bank Sta=355.8,384.9
XS Rating Curve= 0 ,0
Exp/Cntr=0.3,0.1

Type RM Length L Ch R = 1 ,6522.5  ,622.4,568.4,513.3
XS GIS Cut Line= 6
     1765385.721      553150.523     1765311.068      552996.009
     1765465.582       552879.69     1765561.068      552778.995
     1765668.707      552657.468     1765568.013      552515.107
#Sta/Elev= 30
       0  668.12     9.5  663.39    28.6  651.79    38.1  647.04    85.8  628.07
   114.4  615.39   123.9  610.19     143  598.17   152.5  593.91   162.1   591.8
   190.9  590.16   210.3  589.91     249  590.98   297.3  590.36     336  587.84
   355.1  587.52     365  587.74   374.3  588.34   392.8  591.04   429.8  592.59
   503.8  591.73   608.8  593.59   666.1  591.09   685.5  594.51   704.9  601.36
   733.9  604.38   743.6  607.61   772.7  621.27   801.7  632.67   840.5  651.38
#Mann= 3 , 0 , 0
       0      .1       0     336    .045       0     365     .08       0
Bank Sta=336,365
XS Rating Curve= 0 ,0
Exp/Cntr=0.3,0.1

Type RM Length L Ch R = 1 ,5954.1  ,306.4,298.5,292
XS GIS Cut Line= 3
     1766010.721      552634.898     1765693.013       552544.62
     1765592.318      552502.954
#Sta/Elev= 30
       0  607.91    19.4  604.49    38.9  601.54    48.6  599.76    58.3  597.61
      68  594.95    77.7  591.59    87.4  588.44    94.7  587.72    97.1  587.48
   106.9   587.4   116.6  587.47  124.57  587.79     136  588.17   165.1  588.93
     204  590.07   310.9  593.84   320.6  595.29   330.3  599.21   339.4  604.32
   348.4  608.76   357.5  610.86   366.6  610.68   375.7  612.44   393.8  621.34
   402.9  624.56     412  627.14   421.1  630.33   430.2  634.37   439.3   639.2
#Mann= 3 , 0 , 0
       0      .1       0    94.7    .045       0  124.57     .08       0
Bank Sta=94.7,124.57
XS Rating Curve= 0 ,0
Exp/Cntr=0.3,0.1

Type RM Length L Ch R = 1 ,5655.6  ,111.2,112.7,112.7
XS GIS Cut Line= 4
     1766224.624      552408.596     1766106.569      552335.679
     1765955.527      552337.416     1765682.958      552262.763
#Sta/Elev= 30
       0  666.51    18.5  657.31    27.8  649.54      37  637.58    46.2  630.04
    55.5  626.88    64.8  625.37      74  623.38   101.8  612.97   120.3  604.96
   129.5  602.18   157.6  594.51   167.1  592.53     186   589.8   195.4  587.89
   204.8  587.01   214.1  587.04   223.7  587.81   233.2  590.34   242.6  593.71
     252  595.62   261.5  596.61   270.9  597.22   309.3  598.69   367.8  599.49
     397   600.2     436  601.99   465.2  604.06     514  605.08   572.4  608.06
#Mann= 3 , 0 , 0
       0      .1       0   195.4    .045       0   223.7      .1       0
Bank Sta=195.4,223.7
XS Rating Curve= 0 ,0
Exp/Cntr=0.3,0.1

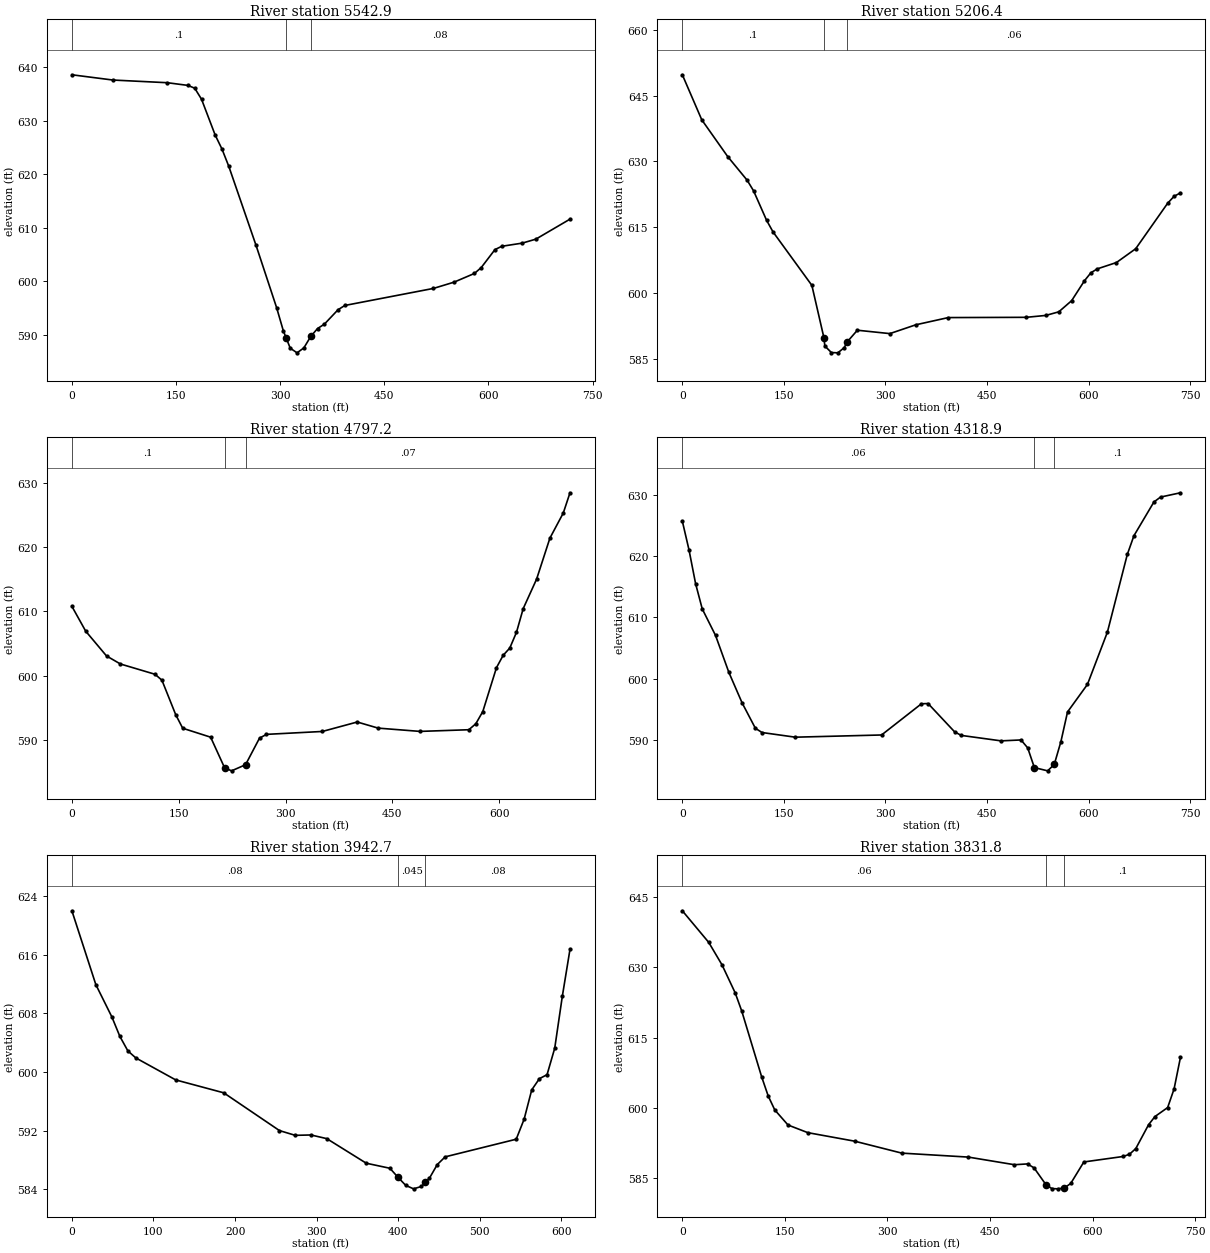
Type RM Length L Ch R = 1 ,5542.9  ,346.4,336.5,325.8
XS GIS Cut Line= 2
     1766401.708      552233.249     1765684.332      552235.593
#Sta/Elev= 30
       0  638.53      59  637.55   137.6  637.05   167.1  636.55   176.9  636.03
   186.7  633.98   206.4  627.29   216.2  624.68     226  621.46   265.3  606.71
   294.8  595.15   304.6  590.78   308.5  589.52   314.5  587.57   324.3   586.7
   334.1  587.62     344  589.75   353.8  591.23   363.6  592.04   383.3  594.73
   393.1  595.53   520.8  598.71   550.3  599.87   579.8   601.5   589.6   602.6
   609.3  605.94   619.1  606.56   648.6  607.15   668.2  607.89   717.4  611.62
#Mann= 3 , 0 , 0
       0      .1       0   308.5    .045       0     344     .08       0
Bank Sta=308.5,344
XS Rating Curve= 0 ,0
Exp/Cntr=0.3,0.1

Type RM Length L Ch R = 1 ,5206.4  ,404.5,409.2,414.5
XS GIS Cut Line= 4
     1766340.944      551886.027      1766149.61      551884.898
      1765814.54      552051.565     1765644.402      552055.037
#Sta/Elev= 30
       0  649.75    28.7  639.49      67  631.12    95.7  625.74   105.2  623.32
   124.4  616.62   133.9  613.97   191.3  601.79  209.03  589.91   210.5  587.97
   220.1  586.49   229.7  586.42   239.3  587.63  243.05  588.84   258.5  591.57
   306.5   590.8   344.9  592.81   392.8  594.45     508  594.51   536.8  594.94
     556  595.76     575   598.3   593.9  602.83   603.4  604.65   612.8  605.54
   641.2  606.99   669.6  610.13   716.8  620.49   726.3  622.07   735.7  622.85
#Mann= 3 , 0 , 0
       0      .1       0  209.03    .045       0  243.05     .06       0
Bank Sta=209.03,243.05
XS Rating Curve= 0 ,0
Exp/Cntr=0.3,0.1

Type RM Length L Ch R = 1 ,4797.2  ,471.1,478.3,485
XS GIS Cut Line= 4
     1766182.596       551535.94     1766038.499       551513.37
     1765620.096      551652.259     1765519.402      551702.607
#Sta/Elev= 30
       0  610.77    19.4  606.91    48.6  603.06    68.1  601.81   116.7  600.21
   126.4  599.29   145.8  593.92   155.6  591.82   194.8  590.43   214.4  585.67
   224.2   585.2   243.8  586.15   263.4  590.28   273.2  590.87   351.6  591.32
   400.6  592.79     430  591.84   488.7  591.33   557.3  591.59   567.1  592.52
   576.9  594.42   596.1  601.24   605.5  603.16   614.8  604.29   624.2  606.74
   633.6  610.41   652.4  614.99   671.1  621.37   689.9  625.28   699.3  628.42
#Mann= 3 , 0 , 0
       0      .1       0   214.4    .045       0   243.8     .07       0
Bank Sta=214.4,243.8
XS Rating Curve= 0 ,0
Exp/Cntr=0.3,0.1

Type RM Length L Ch R = 1 ,4318.9  ,363,376.2,389
XS GIS Cut Line= 2
     1766159.086       551256.86     1765423.409      551243.839
#Sta/Elev= 30
       0  625.67     9.8  621.02    19.6  615.49    29.4  611.39      49  607.08
    68.7  601.06    88.3  596.08   107.9  591.95   117.7  591.26   166.8   590.5
   294.3  590.86   353.2  595.94     363  595.98   402.2  591.37     412  590.79
   470.9   589.9   500.3  590.05   510.2  588.75     520  585.55   539.6  585.02
   549.4  586.06   559.2  589.77     569  594.61   598.4  599.09   627.9  607.61
   657.3  620.26   667.1  623.31   696.6   628.8   706.4   629.6   735.8   630.3
#Mann= 3 , 0 , 0
       0     .06       0     520    .045       0   549.4      .1       0
Bank Sta=520,549.4
XS Rating Curve= 0 ,0
Exp/Cntr=0.3,0.1

Type RM Length L Ch R = 1 ,3942.7  ,114,110.9,101.6
XS GIS Cut Line= 4
       1766188.6       551044.62     1765954.225      551027.259
       1765688.6      550850.176     1765633.044      550841.495
#Sta/Elev= 30
       0  622.02    29.4  611.92      49  607.52    58.8  604.86    68.6  602.88
    78.3  601.92   127.3  598.91   186.1  597.15   254.4  591.99   273.7  591.34
   293.1  591.39   312.4  590.89   360.8  587.53   389.8  586.84   399.5  585.63
   409.2   584.5   418.8  584.03   428.5  584.36   433.2   584.9   438.2  585.48
   447.8  587.34   457.5   588.4   544.6  590.81   554.3  593.55   563.6  597.55
     573  599.08   582.4  599.63   591.8  603.25   601.1  610.33   610.5  616.75
#Mann= 3 , 0 , 0
       0     .08       0   399.5    .045       0   433.2     .08       0
Bank Sta=399.5,433.2
XS Rating Curve= 0 ,0
Exp/Cntr=0.3,0.1

Type RM Length L Ch R = 1 ,3831.8  ,89.3,80.4,77.3
XS GIS Cut Line= 6
     1766316.168      551028.366     1766175.429      550896.008
     1765992.419       550858.64     1765826.404      550827.173
     1765730.918      550820.662     1765647.367      550828.258
#Sta/Elev= 30
       0  642.12    38.6  635.36      58  630.56    77.3  624.56    86.9  620.67
   115.9  606.65   125.6   602.5   135.2  599.52   154.6  596.29   183.5  594.66
   252.2  592.83     321  590.28   418.4  589.43   485.7   587.8   504.9  587.97
   514.5  587.12   531.7  583.56   540.4   582.7     549  582.64   558.6  582.82
   568.1  583.79   587.3  588.39   644.7  589.56     654  590.03   663.3  591.26
     682  596.36   691.3   598.1   709.9  600.03   719.3  604.02   728.6  610.76
#Mann= 3 , 0 , 0
       0     .06       0   531.7    .045       0   558.6      .1       0
Bank Sta=531.7,558.6
XS Rating Curve= 0 ,0
Exp/Cntr=0.3,0.1