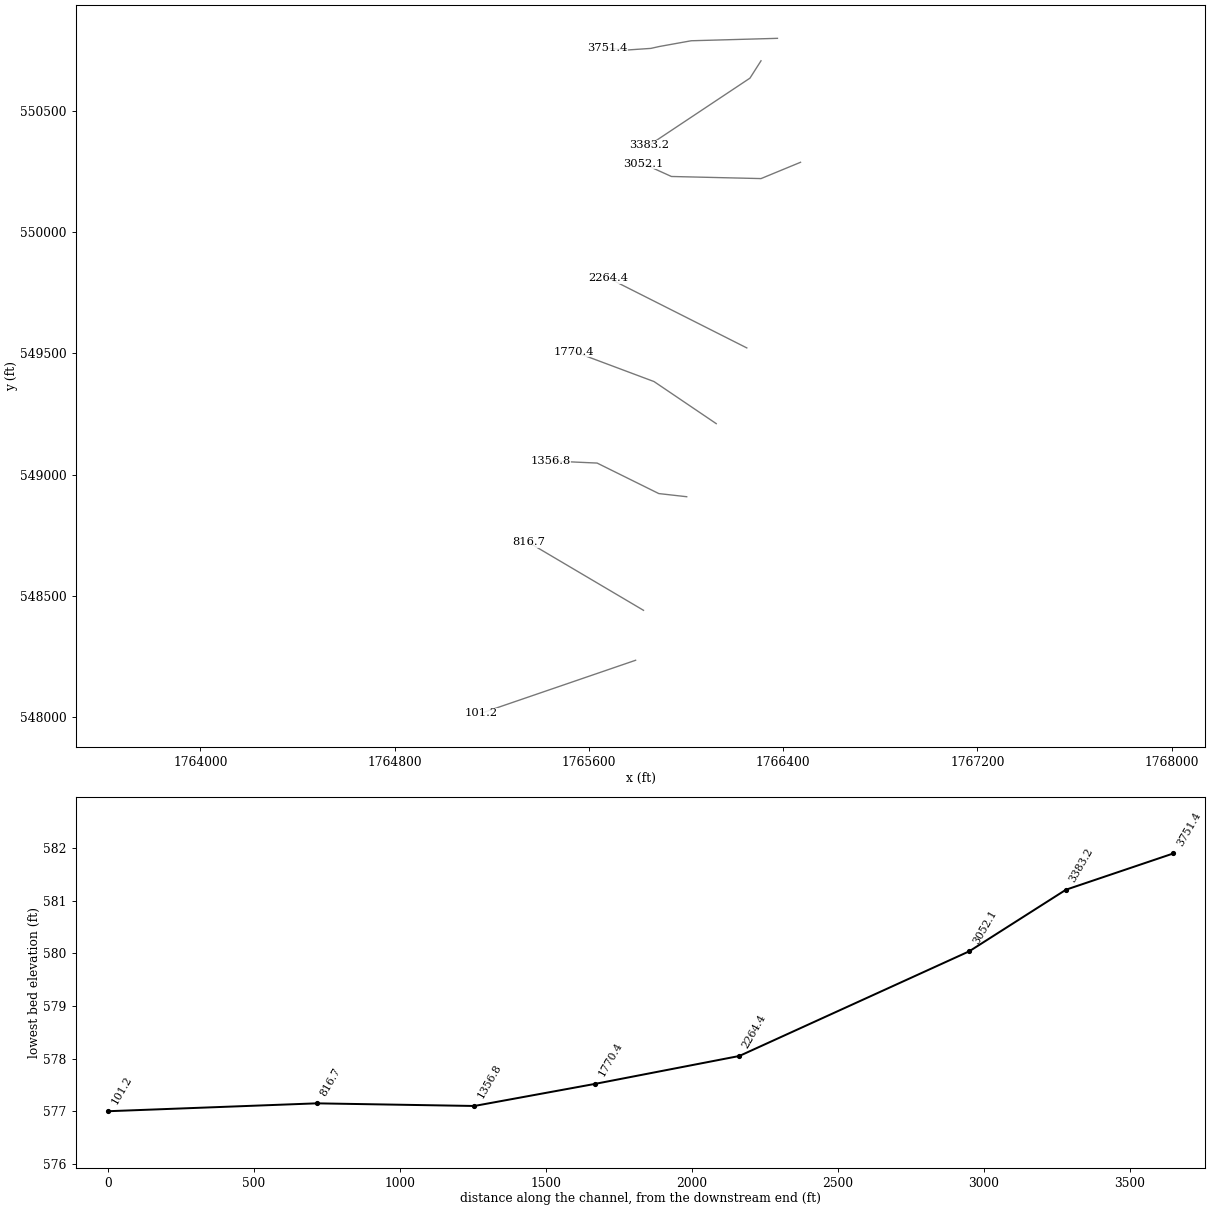
HEC-RAS study FROGCK.prj: FROGCK

--- FROGCK.g01 (geometry) --- (continued)

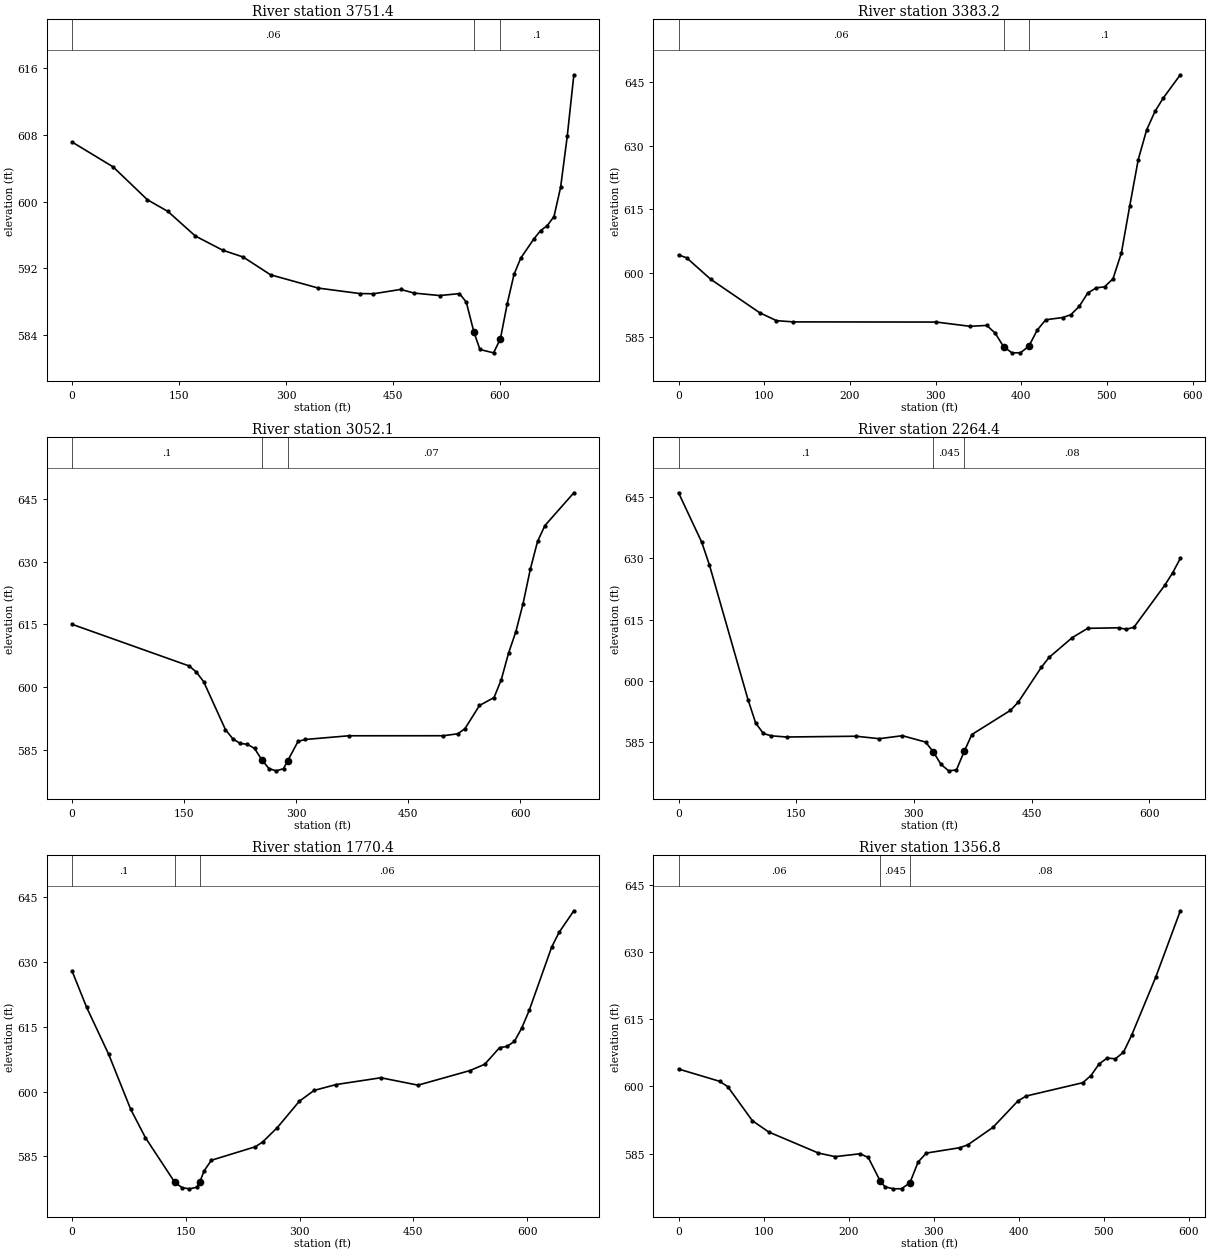
Type RM Length L Ch R = 1 ,3751.4  ,356.4,368.2,380.2
XS GIS Cut Line= 6
     1766376.498      550800.502     1766021.499      550790.497
     1765889.121      550766.626     1765855.484       550759.03
     1765759.998       550752.52     1765676.447      550760.115
#Sta/Elev= 30
       0  607.14    57.6  604.16   105.6  600.23   134.4  598.83   172.8  595.89
   211.2  594.19     240  593.37   278.4  591.24   345.5  589.65   403.2     589
   422.4  588.97   460.8  589.49     480  589.05   515.5  588.76   543.3  588.99
   552.8  587.98  563.69  584.34     572   582.3   591.1   581.9   600.7  583.58
   610.3   587.8   619.8  591.29   629.2  593.24   647.8  595.56   657.1  596.54
   666.4  597.13   675.8  598.21   685.1  601.71   694.4  607.81   703.7  615.19
#Mann= 3 , 0 , 0
       0     .06       0  563.69    .045       0   600.7      .1       0
Bank Sta=563.69,600.7
XS Rating Curve= 0 ,0
Exp/Cntr=0.3,0.1

Type RM Length L Ch R = 1 ,3383.2  ,345,331.1,316.4
XS GIS Cut Line= 3
     1766308.826      550707.815     1766263.253        550636.2
     1765846.586      550358.423
#Sta/Elev= 30
       0  604.28     9.4   603.6    37.7  598.52    94.7  590.66   114.3  588.79
     134   588.5   300.9  588.46   340.2  587.46   359.8  587.67   369.6  585.86
   379.5  582.62   389.3  581.21   399.1  581.23   408.9  582.77   418.7  586.58
   428.6     589   448.2  589.52     458   590.2   467.8  592.19   477.6  595.28
   487.5  596.52   497.3  596.76   507.1  598.65   516.9  604.74   526.7  615.87
   536.6  626.75   546.4  633.73   556.2  638.11     566   641.3   585.7  646.71
#Mann= 3 , 0 , 0
       0     .06       0   379.5    .045       0   408.9      .1       0
Bank Sta=379.5,408.9
XS Rating Curve= 0 ,0
Exp/Cntr=0.3,0.1

Type RM Length L Ch R = 1 ,3052.1  ,799,787.7,774.6
XS GIS Cut Line= 4
     1766471.586      550288.978     1766308.826      550221.704
     1765939.902      550230.384     1765824.885      550282.468
#Sta/Elev= 30
       0  615.02   156.6  605.08   166.3  603.62   176.1  601.31   205.2  589.89
     215  587.71   224.7  586.59   234.4  586.38   244.1  585.41   253.8  582.68
   263.5  580.57   273.2  580.04   282.9  580.55  288.47  582.45   302.4  587.07
   312.1  587.53   370.3  588.41   496.6  588.42     516  588.88   525.7  590.11
   545.1  595.64   564.6  597.54   574.3  601.81     584  608.14   593.7  613.21
   603.4  619.92   613.1  628.14   622.8  634.79   632.6  638.58   671.4  646.42
#Mann= 3 , 0 , 0
       0      .1       0   253.8    .045       0  288.47     .07       0
Bank Sta=253.8,288.47
XS Rating Curve= 0 ,0
Exp/Cntr=0.3,0.1

Type RM Length L Ch R = 1 ,2264.4  ,497.7,494,489.7
XS GIS Cut Line= 2
     1766250.232      549522.919     1765679.485      549811.548
#Sta/Elev= 30
       0  645.94    29.5   633.9    39.4   628.3    88.6   595.4    98.4  589.68
   108.2  587.17   118.1   586.6   137.8  586.31   226.3   586.5   255.8   585.9
   285.4  586.63   314.9  585.07   324.7  582.69   334.6  579.61   344.4  578.05
   354.2  578.27   364.1  582.78   373.9  586.92   423.1  592.82   432.9  594.79
   462.5  603.35   472.3  605.74   501.8  610.57   521.5  612.84   560.9  612.98
   570.7  612.61   580.5  613.12   619.9   623.4   629.7  626.37   639.6  629.93
#Mann= 3 , 0 , 0
       0      .1       0   324.7    .045       0   364.1     .08       0
Bank Sta=324.7,364.1
XS Rating Curve= 0 ,0
Exp/Cntr=0.3,0.1

Type RM Length L Ch R = 1 ,1770.4  ,411,413.7,416.4
XS GIS Cut Line= 3
     1766124.364      549210.419     1765868.288       549384.03
     1765538.426      549507.728
#Sta/Elev= 30
       0  627.83    19.3  619.41    48.3  608.58    77.3   595.9    96.7  589.35
   135.4  579.04     145   577.8   154.7  577.52   164.4  577.89  168.64  579.18
     174  581.64   183.7  584.12   241.7  587.24   251.4  588.35   270.7  591.68
   299.7  597.76   319.2  600.26   348.5  601.62   407.2  603.18   456.2  601.47
   524.7  604.84   544.2   606.3   563.8  610.14   573.6  610.41   583.4   611.6
   593.2  614.74     603  618.83   632.3   633.3   642.1  636.74   661.7  641.75
#Mann= 3 , 0 , 0
       0      .1       0   135.4    .045       0  168.64     .06       0
Bank Sta=135.4,168.64
XS Rating Curve= 0 ,0
Exp/Cntr=0.3,0.1

Type RM Length L Ch R = 1 ,1356.8  ,541.6,540.1,537.4
XS GIS Cut Line= 4
     1766002.836       548908.77     1765887.819      548921.791
     1765633.913      549047.659      1765442.94      549056.339
#Sta/Elev= 30
       0  603.89    48.2  601.15    57.9  599.95    86.8  592.34   106.1  589.81
   164.6   585.1   184.2   584.3   213.5  584.94   223.2  584.11  237.02  578.93
   242.8  577.57   252.6   577.1   262.3  577.13   272.1  578.42   281.9  583.12
   291.6   585.1   330.7  586.29   340.5  586.96   369.8  590.83   399.1  596.72
   408.7  597.84   475.6  600.83   485.2  602.44   494.7     605   504.3  606.36
   513.8  606.16   523.4  607.63     533  611.43   561.6  624.54   590.3  639.27
#Mann= 3 , 0 , 0
       0     .06       0  237.02    .045       0   272.1     .08       0
Bank Sta=237.02,272.1
XS Rating Curve= 0 ,0
Exp/Cntr=0.3,0.1

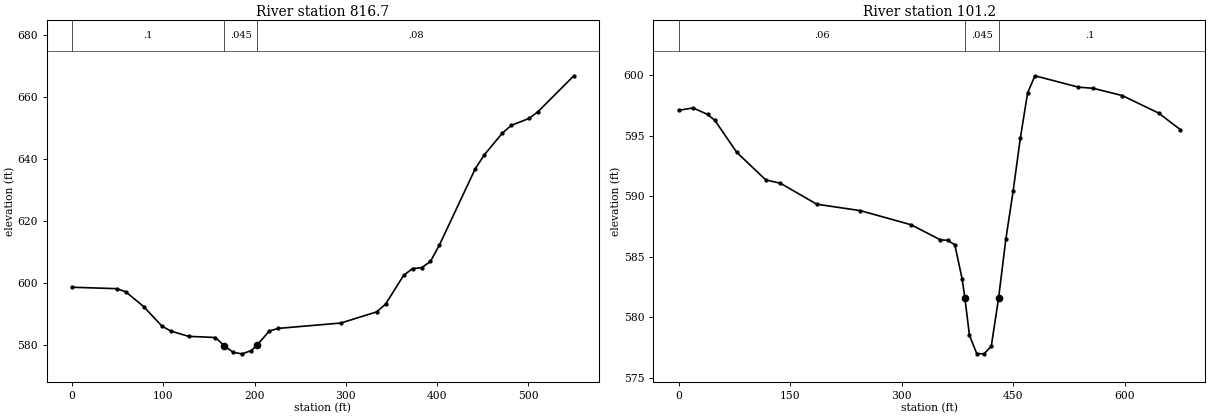
Type RM Length L Ch R = 1 ,816.7   ,696.4,715.4,733.5
XS GIS Cut Line= 2
     1765824.885       548440.02     1765351.794      548719.968
#Sta/Elev= 30
       0  598.65    49.1  598.19    58.9  597.15    78.5   592.4    98.2  586.17
     108  584.52   127.6   582.8   157.1  582.42   166.9  579.69   176.7  577.59
   186.5  577.15   196.3  578.21  202.48   579.9     216   584.5   225.8  585.36
   294.5   587.1   333.8  590.71   343.6  593.26   363.2  602.48     373  604.68
   382.8  604.93   392.6  606.97   402.5  612.33   441.7  636.91   451.6  641.38
   471.2  648.36     481  650.89   500.6  653.14   510.4  655.32   549.7  666.92
#Mann= 3 , 0 , 0
       0      .1       0   166.9    .045       0  202.48     .08       0
Bank Sta=166.9,202.48
XS Rating Curve= 0 ,0
Exp/Cntr=0.3,0.1

Type RM Length L Ch R = 1 ,101.2   ,97.2,101.2,105.4
XS GIS Cut Line= 2
     1765792.333      548233.857     1765154.312      548014.673
#Sta/Elev= 30
       0  597.08    19.6  597.28    39.1  596.74    48.9  596.25    78.2  593.62
   117.3  591.34   136.9  591.07   185.8  589.34   244.4  588.81   312.9  587.64
     352   586.4   361.8  586.36   371.5  585.99   381.3  583.16  385.03  581.57
   391.1  578.53   400.9  577.02   410.6     577   420.4  577.61   430.2  581.57
     440  586.44   449.8  590.41   459.5  594.78   469.3  598.52   479.1  599.93
   537.7  598.99   557.3   598.9   596.4   598.3   645.3  596.86   674.6  595.49
#Mann= 3 , 0 , 0
       0     .06       0  385.03    .045       0   430.2      .1       0
Bank Sta=385.03,430.2
XS Rating Curve= 0 ,0
Exp/Cntr=0.3,0.1

Chan Stop Cuts=-1
Use User Specified Reach Order=0
Composite Channel Slope=5